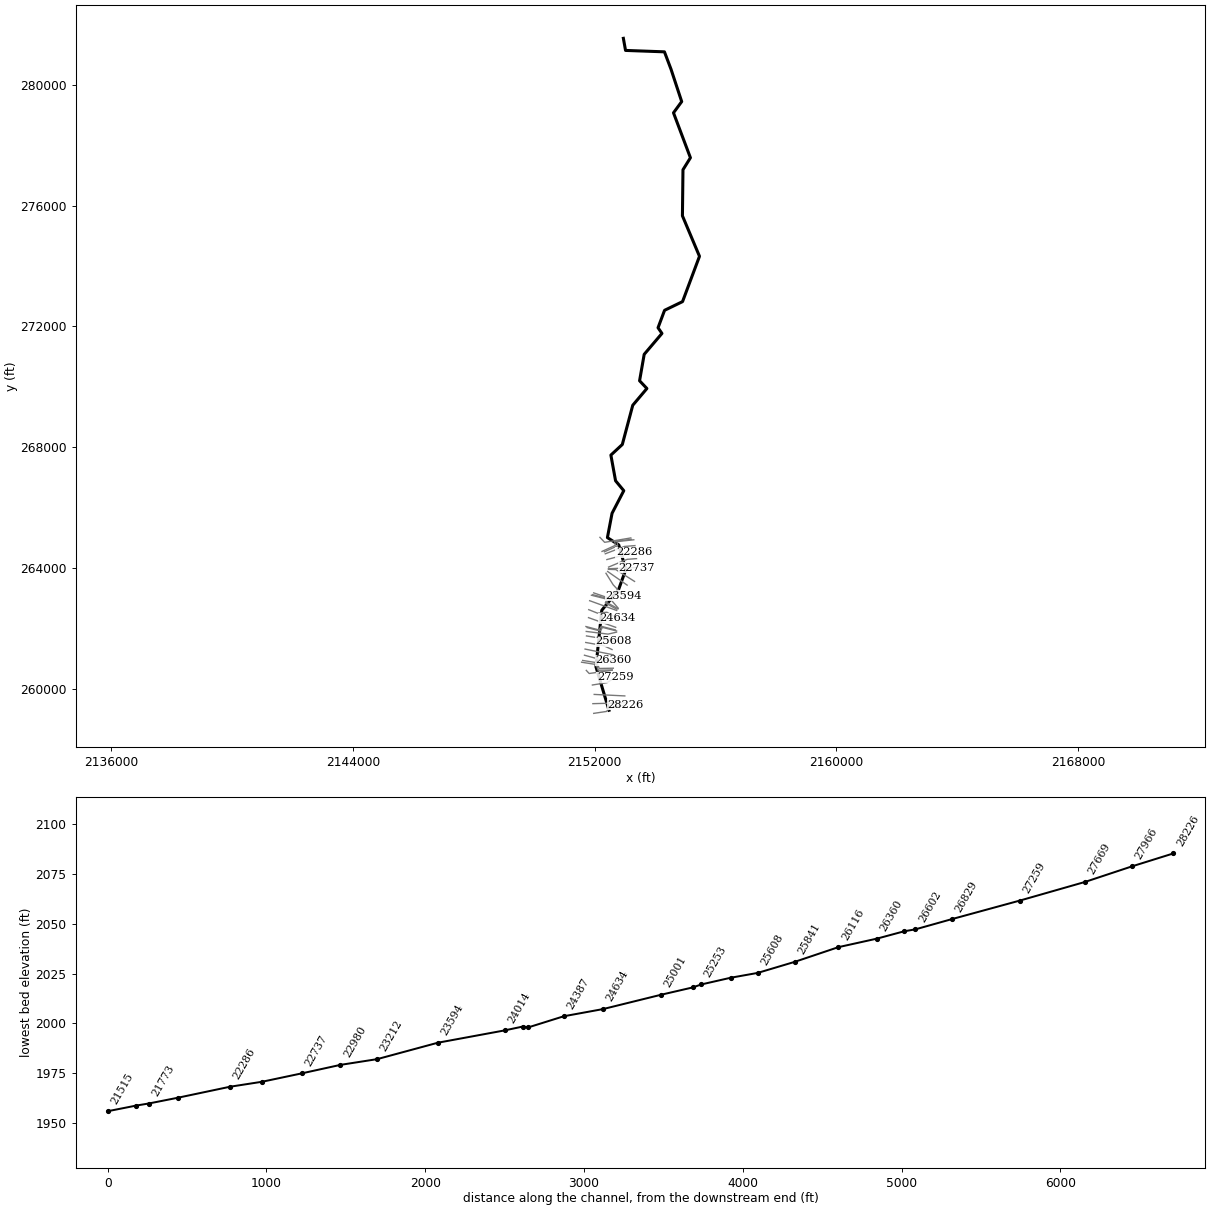
--- HARTSRN.prj (project) ---

Proj Title=HARTSRN
Current Plan=p01
Default Exp/Contr=0,0
English Units
Geom File=g01
Flow File=f01
Plan File=p01
BEGIN DESCRIPTION:
Stream Name- Harts Run
Flood Zone: Zone A
Greenbrier County, WV
County-Wide Study
WVDHSEM-2018-3, Flood Risk Project
HEC-RAS Version: 5.0.7
General Notes:
For the Hydrology HECHMS 4.2.1 was used.
END DESCRIPTION:
DSS Export Rating Curves= 0
DSS Export Rating Curve Sorted= 0
DSS Export Volume Flow Curves= 0
DXF OffsetX= 0
DXF OffsetY= 0
DXF ScaleX= 0
DXF ScaleY= 0

--- HARTSRN.p01 (plan) ---

Plan Title=Floodplain
Program Version=5.07
Short Identifier=Floodplain
Geom File=g01
Flow File=f01
Subcritical Flow
K Sum by GR= 0
Std Step Tol= 0.01
Critical Tol= 0.01
Num of Std Step Trials= 20
Max Error Tol= 0.3
Flow Tol Ratio= 0.001
Split Flow NTrial= 30
Split Flow Tol= 0.02
Split Flow Ratio= 0.02
Log Output Level= 0
Friction Slope Method= 1
Unsteady Friction Slope Method= 2
Unsteady Bridges Friction Slope Method= 1
Parabolic Critical Depth
Global Vel Dist= 0 , 0 , 0
Global Log Level= 0
CheckData=True
Encroach Param=-1 ,0,0, 0
Mapping Interval=1HOUR
Computation Time Step Use Courant=        0
Computation Time Step Use Time Series=    0
Computation Time Step Count To Double=0
Computation Time Step Max Doubling=0
Computation Time Step Max Halving=0
Computation Time Step Residence Courant=0
Run HTab= 0
Run UNet= 0
Run Sediment= 0
Run PostProcess= 0
Run WQNet= 0
Run RASMapper= 0
UNET Theta= 0
UNET Theta Warmup= 0
UNET ZTol= 0
UNET ZSATol= 0
UNET MxIter= 0
UNET Max Iter WO Improvement= 0
UNET MaxInSteps= 0
UNET DtIC= 0
UNET DtMin= 0
UNET MaxCRTS= 0
UNET WFStab= 0
UNET SFStab= 0
UNET WFX= 1
UNET SFX= 1
UNET 1D Methodology=Finite Difference
UNET DSS MLevel= 1
UNET Pardiso=0
UNET DZMax Abort= 0
UNET Use Existing IB Tables= 0
UNET Froude Reduction=False
UNET Froude Limit= 0
UNET Froude Power= 0
UNET D1 Cores= 0
UNET D2 Coriolis=0
UNET D2 Cores= 0
UNET D2 Theta= 1
UNET D2 Theta Warmup= 1
UNET D2 Z Tol= 0.01
UNET D2 Volume Tol= 0.01
UNET D2 Max Iterations= 20
UNET D2 Equation= 0
UNET D2 RampUpFraction=0.1
UNET D2 TimeSlices= 1
UNET D2 BCVolumeCheck=0
UNET D1D2 MaxIter= 0
UNET D1D2 ZTol=0.01
UNET D1D2 QTol=0.1
UNET D1D2 MinQTol=1
Write IC File= 0
Write IC File at Fixed DateTime=0
Write IC File at Sim End=0
Echo Input=False
Echo Parameters=False
Echo Output=False
Write Detailed= 0
HDF Write Warmup=0
HDF Write Time Slices=0
HDF Flush=0
HDF Face Node Velocities=0
HDF Compression= 1
HDF Chunk Size= 1
HDF Spatial Parts= 1
HDF Use Max Rows=0
HDF Fixed Rows= 1
Calibration Method= 0
Calibration Iterations= 20
Calibration Max Change=0.05
Calibration Tolerance=0.2
Calibration Maximum=1.5
Calibration Minimum=0.5
Calibration Optimization Method= 1
WQ AD Non Conservative
WQ ULTIMATE=-1
WQ Max Comp Step=1HOUR
WQ Output Interval=15MIN
WQ Output Selected Increments= 0
WQ Output face flow=0
WQ Output face velocity=0
WQ Output face area=0
WQ Output face dispersion=0
WQ Output cell volume=0
WQ Output cell surface area=0
WQ Output cell continuity=0
WQ Output cumulative cell continuity=0
WQ Output face conc=0
WQ Output face dconc_dx=0
WQ Output face courant=0
WQ Output face peclet=0
WQ Output face adv mass=0
WQ Output face disp mass=0
WQ Output cell mass=0
WQ Output cell source sink temp=0
WQ Output nsm pathways=0
WQ Output nsm derived pathways=0
WQ Output MaxMinRange=-1
WQ Daily Max Min Mean=-1
WQ Daily Range=0
WQ Daily Time=0
WQ Create Restart=0
WQ Fixed Restart=0
WQ System Summary=0
WQ Write To DSS=0
WQ Use Fixed Temperature=0
Sorting and Armoring Iterations= 10
XS Update Threshold= 0.02
Bed Roughness Predictor= 0
Hydraulics Update Threshold= 0.02
Energy Slope Method= 1
Volume Change Method= 1
Sediment Retention Method= 0
XS Weighting Method= 0
Number of US Weighted Cross Sections= 1
Number of DS Weighted Cross Sections= 1
Upstream XS Weight=0
Main XS Weight=1
Downstream XS Weight=0
Number of DS XS's Weighted with US Boundary= 1
Upstream Boundary Weight= 1
Weight of XSs Associated with US Boundary= 0
Number of US XS's Weighted with DS Boundary= 1
Downstream Boundary Weight= 0.5
Weight of XSs Associated with DS Boundary= 0.5
Percentile Method= 0
Sediment Output Level= 3
Mass or Volume Output= 0
Output Increment Type= 1
Profile and TS Output Increment= 1
XS Output Flag= 0
XS Output Increment= 10
Write Gradation File= 0
Read Gradation Hotstart= 0
Write HDF5 File= 1
Write Binary Output= 1
Write DSS Sediment File= 0
SV Curve= 0
Specific Gage Flag= 0

--- HARTSRN.f01 (steady flow) ---

Flow Title=WV Regression w 2016/2010 Gage Weighting
Program Version=5.07
Number of Profiles= 6
Profile Names=f1p,f10p,f4p,f2p,f02p,f1pplus
River Rch & RM=HARTSRN,Main            ,28226
     583     308     410     494     814     862
River Rch & RM=HARTSRN,Main            ,26360
     648     344     457     549     903     958
River Rch & RM=HARTSRN,Main            ,23212
     723     386     511     613    1010    1070
River Rch & RM=HARTSRN,Main            ,22737
     997     539     709     849    1380    1480
River Rch & RM=HARTSRN,Main            ,21956
    1110     604     793     948    1540    1650
River Rch & RM=HARTSRN,Main            ,18649
    1280     695     911    1090    1760    1890
River Rch & RM=HARTSRN,Main            ,15582
    1460     801    1050    1250    2010    2160
River Rch & RM=HARTSRN,Main            ,12989
    1660     916    1190    1420    2280    2460
River Rch & RM=HARTSRN,Main            ,8715
    1930    1070    1390    1650    2630    2850
River Rch & RM=HARTSRN,Main            ,7255
    2150    1200    1550    1840    2930    3180
Boundary for River Rch & Prof#=HARTSRN,Main            , 1
Up Type= 0
Dn Type= 3
Dn Slope=0.00429
Boundary for River Rch & Prof#=HARTSRN,Main            , 2
Up Type= 0
Dn Type= 3
Dn Slope=0.00429
Boundary for River Rch & Prof#=HARTSRN,Main            , 3
Up Type= 0
Dn Type= 3
Dn Slope=0.00429
Boundary for River Rch & Prof#=HARTSRN,Main            , 4
Up Type= 0
Dn Type= 3
Dn Slope=0.00429
Boundary for River Rch & Prof#=HARTSRN,Main            , 5
Up Type= 0
Dn Type= 3
Dn Slope=0.00429
Boundary for River Rch & Prof#=HARTSRN,Main            , 6
Up Type= 0
Dn Type= 3
Dn Slope=0.00429
DSS Import GetInterval= 0
DSS Import GetPeak= 0
DSS Import FillOption= 0

--- HARTSRN.g01 (geometry) ---

Geom Title=USGS 1m DEM
Program Version=5.07

River Reach=HARTSRN         ,Main
Reach XY= 30
     2152475.608259287.585999999    2152044.4249260726.975400001
      2152236.73      262598.645    2152791.3903263279.885399999
      2153031.11263945.778999999     2152798.902      264766.168
    2152423.3542     265006.4649     2152577.065      265811.793
     2152965.308      266561.044     2152693.218      266889.285
      2152538.45       267739.58     2152916.489      268090.566
     2153262.437      269390.554     2153730.763269945.552999999
      2153488.11270201.857000001      2153640.98271077.030999999
    2154228.9872     271769.7784    2154099.2376271957.874700001
     2154315.221      272535.364    2154910.6311      272823.624
      2155471.44274324.381999999     2154906.842      275665.411
      2154924.69      277191.248    2155171.4462277588.902100001
     2154611.034      279077.204     2154882.618      279448.872
      2154528.91280521.811000001    2154311.1722     281097.2403
     2153023.702      281143.7722152951.74046946       281544.27

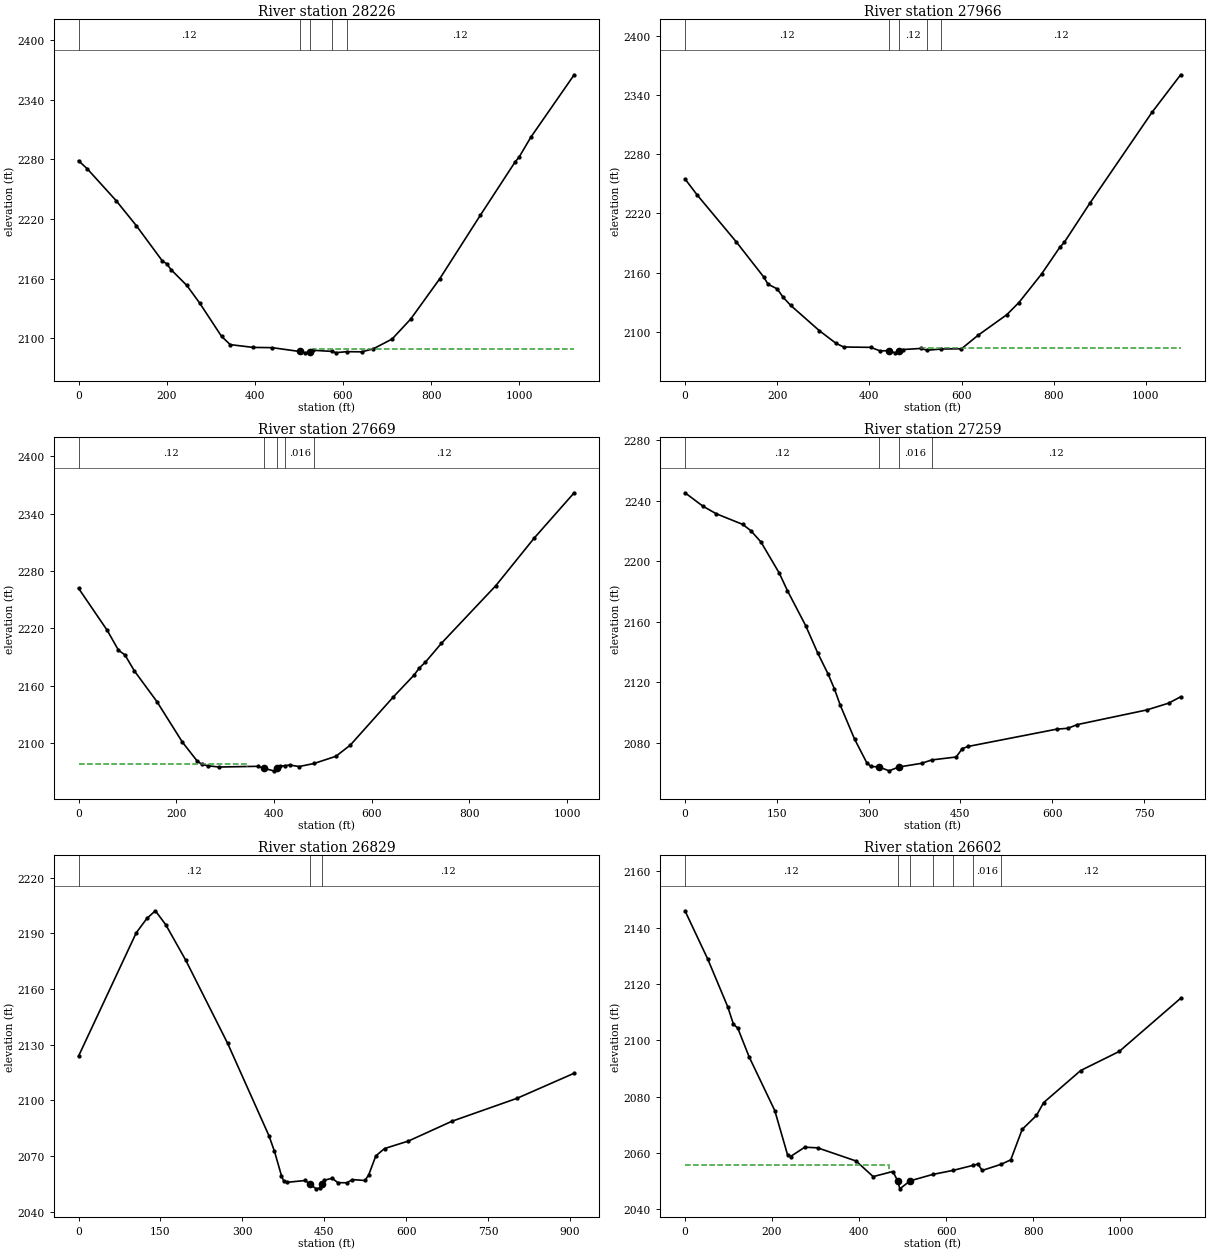
Type RM Length L Ch R = 1 ,28226   ,260.7,260.7,260.7
XS GIS Cut Line= 4
     2151970.224      259184.646     2152391.446      259248.227
     2152502.712      259359.493     2153033.213      259464.799
#Sta/Elev= 30
       0 2278.69    19.7 2270.59    85.2 2238.56   131.1 2213.33   190.1 2177.85
   199.9 2175.01   209.7 2169.13   245.8  2153.1   275.3 2135.09   324.4 2101.91
   344.1  2093.6   396.5 2090.78   439.1 2090.55   501.4 2086.71   514.5 2085.33
   524.3 2086.66   530.9 2087.95  575.88 2086.75   583.4  2085.5  608.082086.489
   642.4 2086.35   668.6 2089.38   711.2  2099.2   753.8 2119.52   819.4 2159.94
   911.1  2223.6   989.8 2277.13   999.6 2282.54  1025.9 2302.31  1124.2 2365.15
#Mann= 5 ,-1 , 0
       0     .12       0   501.4     .04       0   524.3     .12       0
  575.88    .016       0  608.08     .12       0
#XS Ineff= 2 , 0
                          530.36         2089.32
Permanent Ineff=
       F       F
Bank Sta=501.4,524.3
XS Rating Curve= 0 ,0
Exp/Cntr=0.3,0.1

Type RM Length L Ch R = 1 ,27966   ,296.9,296.9,296.9
XS GIS Cut Line= 2
     2151942.408      259506.523     2153017.318       259534.34
#Sta/Elev= 30
       0    2255    26.2 2238.87   111.5 2191.11   170.5 2155.86   180.3  2148.3
     200 2143.64   213.1 2135.04   229.5 2126.82   291.8 2101.17   327.8 2088.43
   344.2 2084.77   403.2 2084.38   422.9 2080.86   442.6 2080.98   455.7 2078.84
  465.34  2080.6   472.1 2082.15   511.4 2083.29  525.652081.482   555.22082.719
   599.9 2082.97     636 2096.68   698.3 2117.52   724.5 2129.82   773.7 2158.73
     813 2185.62   822.8 2190.71   878.6 2230.54    1013 2322.31  1075.3 2360.46
#Mann= 5 ,-1 , 0
       0     .12       0   442.6     .04       0  465.34     .12       0
  525.65    .016       0   555.2     .12       0
#XS Ineff= 2 , 0
                          509.84         2083.99
Permanent Ineff=
       F       F
Bank Sta=442.6,465.34
XS Rating Curve= 0 ,0
Exp/Cntr=0.3,0.1

Type RM Length L Ch R = 1 ,27669   ,408.5,408.5,408.5
XS GIS Cut Line= 2
     2151986.119      259812.505     2152999.436      259762.833
#Sta/Elev= 30
       0 2261.99    58.9 2217.84    81.8 2197.15    94.9 2192.32   114.5 2175.41
   160.4 2143.47   212.7 2100.96   242.2 2081.71     252 2077.86   265.1 2076.22
     288    2075   366.5 2075.72  378.762073.765   399.3 2070.99   406.72073.767
   412.4 2075.85  423.182076.428     432 2077.08   451.6  2075.5  482.322078.706
   526.9 2086.23   556.4 2097.95   644.7 2148.46   687.3 2171.47   697.1 2178.32
   710.2 2184.79   742.9 2204.46   854.2 2264.74   932.7 2314.46  1014.5 2361.85
#Mann= 5 ,-1 , 0
       0     .12       0  378.76     .04       0   406.7     .12       0
  423.18    .016       0  482.32     .12       0
#XS Ineff= 2 , 0
          344.77 2078.14
Permanent Ineff=
       F       F
Bank Sta=378.76,406.7
XS Rating Curve= 0 ,0
Exp/Cntr=0.3,0.1

Type RM Length L Ch R = 1 ,27259   ,430.9,430.9,430.9
XS GIS Cut Line= 3
     2151926.513      260124.4482152413.20756159260202.553836608
 2152679.8351738260373.847371415
#Sta/Elev= 30
       0 2245.11  29.459 2236.24  51.053 2231.29   94.252224.261 107.5412220.147
 124.1552212.629  154.062192.103 167.3522180.561 197.2572157.417 217.1942139.141
 233.8082125.566 244.2072115.716 253.745 2104.94 277.0042082.702 296.941 2067.07
 303.5872064.626  317.622064.179 333.4922061.682  349.022064.179 386.6572066.656
 403.2712068.881 443.1452070.811 453.1142076.359 463.0822077.805 607.2112089.169
 625.5832089.757 641.1822092.204 754.4132101.837 790.0272106.297 809.8322110.522
#Mann= 4 ,-1 , 0
       0     .12       0  317.62     .04       0  349.02    .016       0
 403.271     .12       0
Bank Sta=317.62,349.02
XS Rating Curve= 0 ,0
Exp/Cntr=0.3,0.1

Type RM Length L Ch R = 1 ,26829   ,227.5,227.5,227.5
XS GIS Cut Line= 3
2151724.28611551260608.335592218      2151820.12       260505.37
     2152579.235      260613.443
#Sta/Elev= 30
       0 2123.79   105.6 2190.24   125.2 2198.05   140.7 2202.16   159.7 2194.65
   196.3 2175.53     273 2130.71   348.8 2080.83   358.7 2072.56   371.6 2059.33
   375.3 2056.76   381.9 2055.82   415.1 2056.81  423.172054.838   435.4 2052.31
   441.5  2052.8  445.652054.834   449.9 2056.96   464.4 2058.01   474.7 2055.65
   491.3 2055.57   501.2 2057.29   524.4 2056.81   531.2  2059.8   544.3 2070.07
   560.2 2074.02   603.9 2078.06   683.5 2088.72   802.8  2101.1   907.4 2114.61
#Mann= 3 , 0 , 0
       0     .12       0  423.17     .04       0  445.65     .12       0
#XS Ineff= 2 , 0
                          464.17         2057.93
Permanent Ineff=
       F       F
Bank Sta=423.17,445.65
XS Rating Curve= 0 ,0
Exp/Cntr(USF)=0,0
Exp/Cntr=0.5,0.3

Type RM Length L Ch R = 1 ,26602   ,72.1,72.1,72.1
XS GIS Cut Line= 5
     2151568.818      260879.068     2151989.391      260812.661
     2152075.329      260734.536     2152115.693      260613.443
     2152584.443      260622.557
#Sta/Elev= 30
       0 2145.94    52.4 2128.75    98.3 2111.82   111.4 2105.61   121.2  2104.3
   147.4 2094.05   206.3 2074.99   235.8 2059.19   242.4 2058.69   275.1    2062
   304.6 2061.78     393  2057.1   432.2 2051.57   477.4 2053.37  488.572050.062
   493.5 2047.22  517.112050.062  568.772052.322  615.66 2053.77   662.2 2055.58
   672.8 2056.02   682.7 2053.76  726.322055.945   748.2 2057.52   774.5 2068.33
   807.3 2073.27   823.7 2077.83   908.9 2089.23   997.4    2096  1138.4 2114.87
#Mann= 7 ,-1 , 0
       0     .12       0  488.57     .04       0  517.11     .12       0
  568.77    .016       0  615.66     .12       0   662.2    .016       0
  726.32     .12       0
#XS Ineff= 2 , 0
          469.57 2055.67
Permanent Ineff=
       F       F
Bank Sta=488.57,517.11
XS Rating Curve= 0 ,0
Exp/Cntr=0.5,0.3

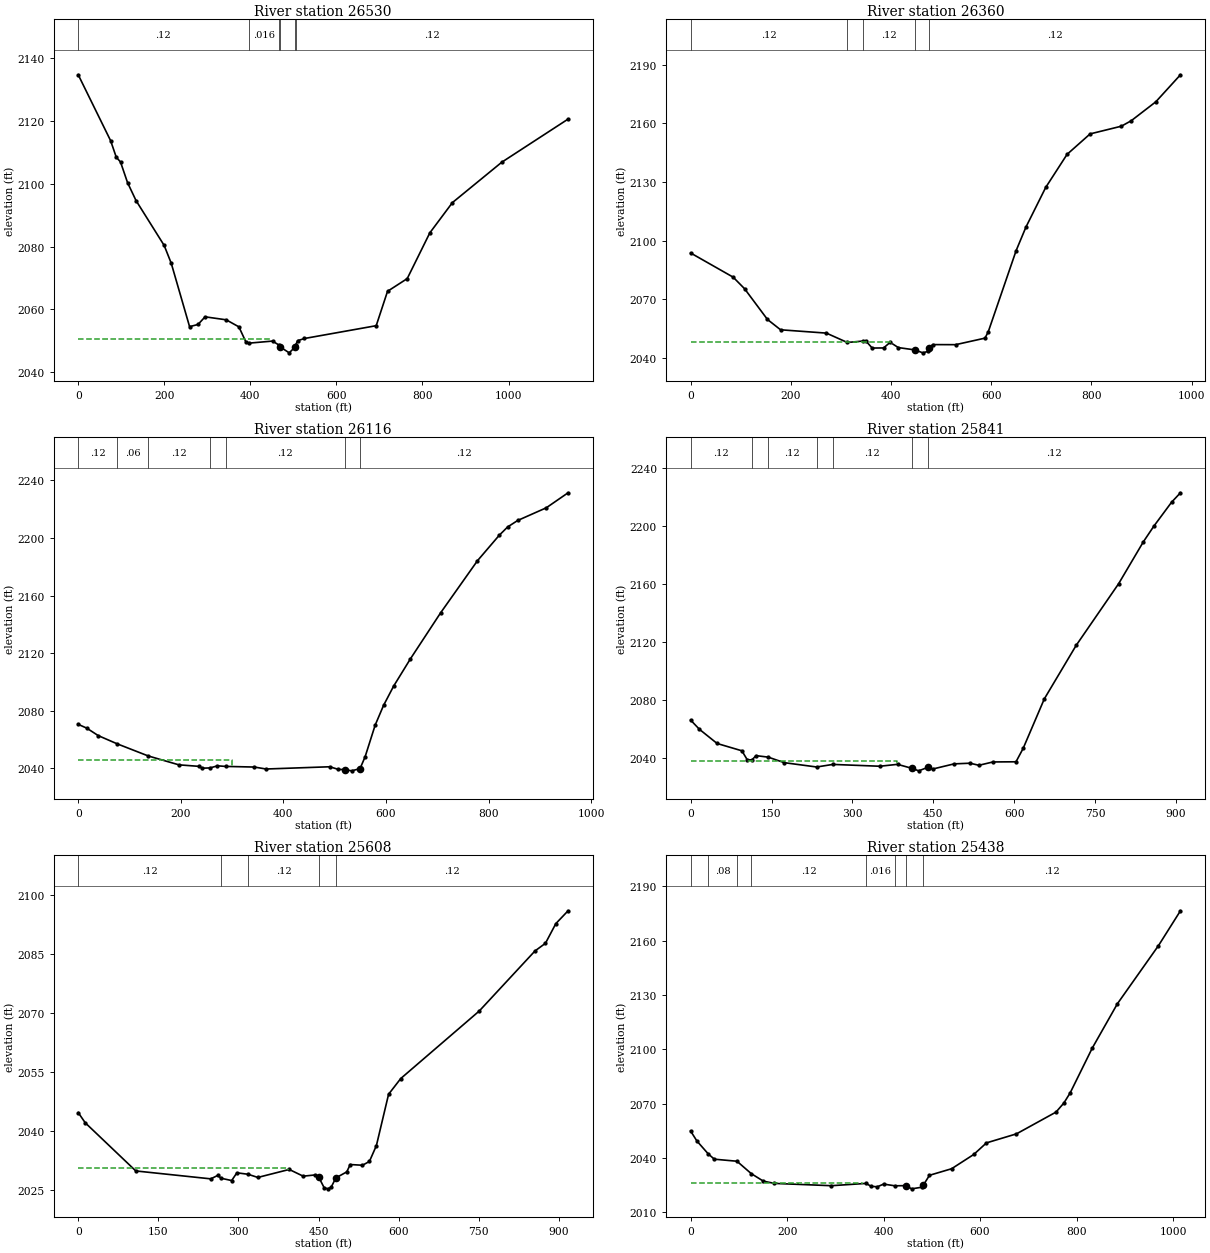
Type RM Length L Ch R = 1 ,26530   ,169.1,169.1,169.1
XS GIS Cut Line= 5
     2151603.974      260937.661     2152024.547      260871.255
     2152110.485       260793.13     2152150.849      260672.036
     2152619.599      260681.151
#Sta/Elev= 30
       0 2134.62    75.3 2113.66    88.4 2108.42    98.3 2106.89   114.6 2100.34
   134.3 2094.64   199.8 2080.35   216.2 2074.69   258.8 2054.54   278.4 2055.24
   294.8 2057.67   343.9 2056.72   373.4 2054.48   389.8 2049.63  396.072049.292
   451.6 2049.96  465.952048.741  469.152048.124   490.3 2046.22  504.472048.125
  505.882048.852   509.7 2050.08   525.8 2050.78   692.5 2054.85   718.8 2065.78
   764.6 2069.82   817.1 2084.36   869.6 2093.98   984.3 2106.82  1138.4 2120.53
#Mann= 6 ,-1 , 0
       0     .12       0  396.07    .016       0  465.95     .12       0
  469.15     .04       0  504.47    .016       0  505.88     .12       0
#XS Ineff= 2 , 0
          444.78 2050.53
Permanent Ineff=
       F       F
Bank Sta=469.15,504.47
XS Rating Curve= 0 ,0
Exp/Cntr=0.5,0.3

Type RM Length L Ch R = 1 ,26360   ,244.3,244.3,244.3
XS GIS Cut Line= 3
      2151663.87      261110.838     2152265.433      260946.776
     2152619.599      260941.568
#Sta/Elev= 30
       0 2093.71    84.9 2081.33   107.7 2075.41   153.4 2059.67   179.6 2054.38
     271 2052.68   312.82047.883  343.422048.598   349.3 2048.82   362.4 2045.03
   385.2 2045.09   398.3 2047.97   414.6 2045.27   447.2  2044.1   463.6 2042.58
   473.4 2043.32   476.6 2045.25   483.2  2046.8   528.9 2046.76   587.6 2050.11
   594.2 2053.44   649.8 2094.97   669.4 2107.01   708.8 2127.28   751.4  2144.2
   797.4 2154.67   859.7 2158.61   879.4  2161.4   928.5  2171.1   977.7 2184.94
#Mann= 5 ,-1 , 0
       0     .12       0   312.8    .016       0  343.42     .12       0
   447.2     .04       0   476.6     .12       0
#XS Ineff= 2 , 0
             402 2048.23
Permanent Ineff=
       F       F
Bank Sta=447.2,476.6
XS Rating Curve= 0 ,0
Exp/Cntr=0.3,0.1

Type RM Length L Ch R = 1 ,26116   ,275.4,275.4,275.4
XS GIS Cut Line= 2
     2151684.111      261314.598     2152619.939      261123.856
#Sta/Elev= 30
       0 2070.55    16.4 2067.96    39.2  2062.7    76.3 2056.97  136.592048.594
   196.2 2042.44   235.5 2041.38     242 2040.11  257.162040.302   271.5 2041.75
  287.312041.348   343.4  2040.9   366.3 2039.54   490.6  2041.1     507 2039.28
     520 2039.12   533.1 2038.27   549.5 2039.84   559.3 2047.96   578.9 2069.94
   595.3 2083.69   614.9 2097.04   647.6 2115.98   706.5 2147.94   778.4 2184.15
     821 2201.87   837.3 2207.61   856.9 2212.11   912.6  2220.9   955.1 2231.33
#Mann= 7 ,-1 , 0
       0     .12       0    76.3     .06       0  136.59     .12       0
  257.16    .016       0  287.31     .12       0     520     .04       0
   549.5     .12       0
#XS Ineff= 2 , 0
          299.03 2045.61
Permanent Ineff=
       F       F
Bank Sta=520,549.5
XS Rating Curve= 0 ,0
Exp/Cntr=0.3,0.1

Type RM Length L Ch R = 1 ,25841   ,232.9,232.9,232.9
XS GIS Cut Line= 3
     2151705.967      261533.156     2152300.049      261427.851
     2152576.227      261298.702
#Sta/Elev= 30
       0 2066.01    16.4 2059.59    49.2 2049.79    95.1 2044.74   104.9 2038.61
  113.712038.423   121.3 2041.39  143.712040.371   173.8 2036.52   233.72033.539
   263.72035.318   350.9 2034.06   383.6 2035.37   409.9 2032.67     423 2030.88
   439.4 2033.27   449.2 2032.16   488.6  2035.7   518.1 2036.16   534.5 2034.72
   560.7 2037.03   603.3 2037.14   616.5 2046.36   655.8 2080.65   714.8 2117.62
   793.5 2160.26   839.4 2189.27     859 2200.17   891.8 2216.69   908.2 2223.19
#Mann= 7 ,-1 , 0
       0     .12       0  113.71     .08       0  143.71     .12       0
   233.7    .016       0   263.7     .12       0   409.9     .04       0
   439.4     .12       0
#XS Ineff= 2 , 0
          383.07 2037.38
Permanent Ineff=
       F       F
Bank Sta=409.9,439.4
XS Rating Curve= 0 ,0
Exp/Cntr=0.3,0.1

Type RM Length L Ch R = 1 ,25608   ,169.6,169.6,169.6
XS GIS Cut Line= 3
     2151730.971      261749.716     2152188.529       261674.84
     2152629.125      261567.296
#Sta/Elev= 30
       0 2044.73    13.1 2042.14   107.8 2029.89   248.2 2027.88   261.2 2028.75
  267.682028.024   287.3 2027.45   297.1 2029.42  317.922029.046   336.3 2028.24
   395.1 2030.27   421.2 2028.56     444 2028.88   450.6 2028.23   460.4 2025.65
   466.9 2025.34   473.4 2025.71  482.452028.127   502.8 2029.65   509.3 2031.52
   532.2 2031.34   545.2  2032.3   558.3 2036.34   581.1 2049.39   603.9 2053.39
   750.8 2070.55   855.2 2085.83   874.8 2087.78   894.3 2092.79   917.2 2096.05
#Mann= 5 ,-1 , 0
       0     .12       0  267.68    .016       0  317.92     .12       0
   450.6     .04       0  482.45     .12       0
#XS Ineff= 2 , 0
          391.98 2030.55
Permanent Ineff=
       F       F
Bank Sta=450.6,482.45
XS Rating Curve= 0 ,0
Exp/Cntr=0.3,0.1

Type RM Length L Ch R = 1 ,25438   ,185.4,185.4,185.4
XS GIS Cut Line= 3
     2151722.464      261898.599      2152445.12      261810.057
     2152725.068      261875.161
#Sta/Elev= 30
       0 2054.85    13.1 2049.33   36.642042.193    49.2 2039.29   96.152038.159
  125.912031.284   150.9 2027.16   173.8 2025.92   291.9 2024.65  363.972025.922
   373.9 2024.32     387 2024.05   400.1 2025.54  423.492024.595     446 2024.69
   458.3 2022.92   478.8 2023.79  482.732025.077   495.2  2030.4   541.1 2034.02
     587  2041.9   613.3 2048.29   675.6 2053.28   757.5 2065.29   773.8  2070.3
   786.8 2075.87   832.6  2100.6   884.8 2125.12   969.8 2157.16  1015.5 2176.45
#Mann= 8 ,-1 , 0
       0     .06       0   36.64     .08       0   96.15     .06       0
  125.91     .12       0  363.97    .016       0  423.49     .12       0
     446     .04       0  482.73     .12       0
#XS Ineff= 2 , 0
          355.24 2026.25
Permanent Ineff=
       F       F
Bank Sta=446,482.73
XS Rating Curve= 0 ,0
Exp/Cntr=0.5,0.3

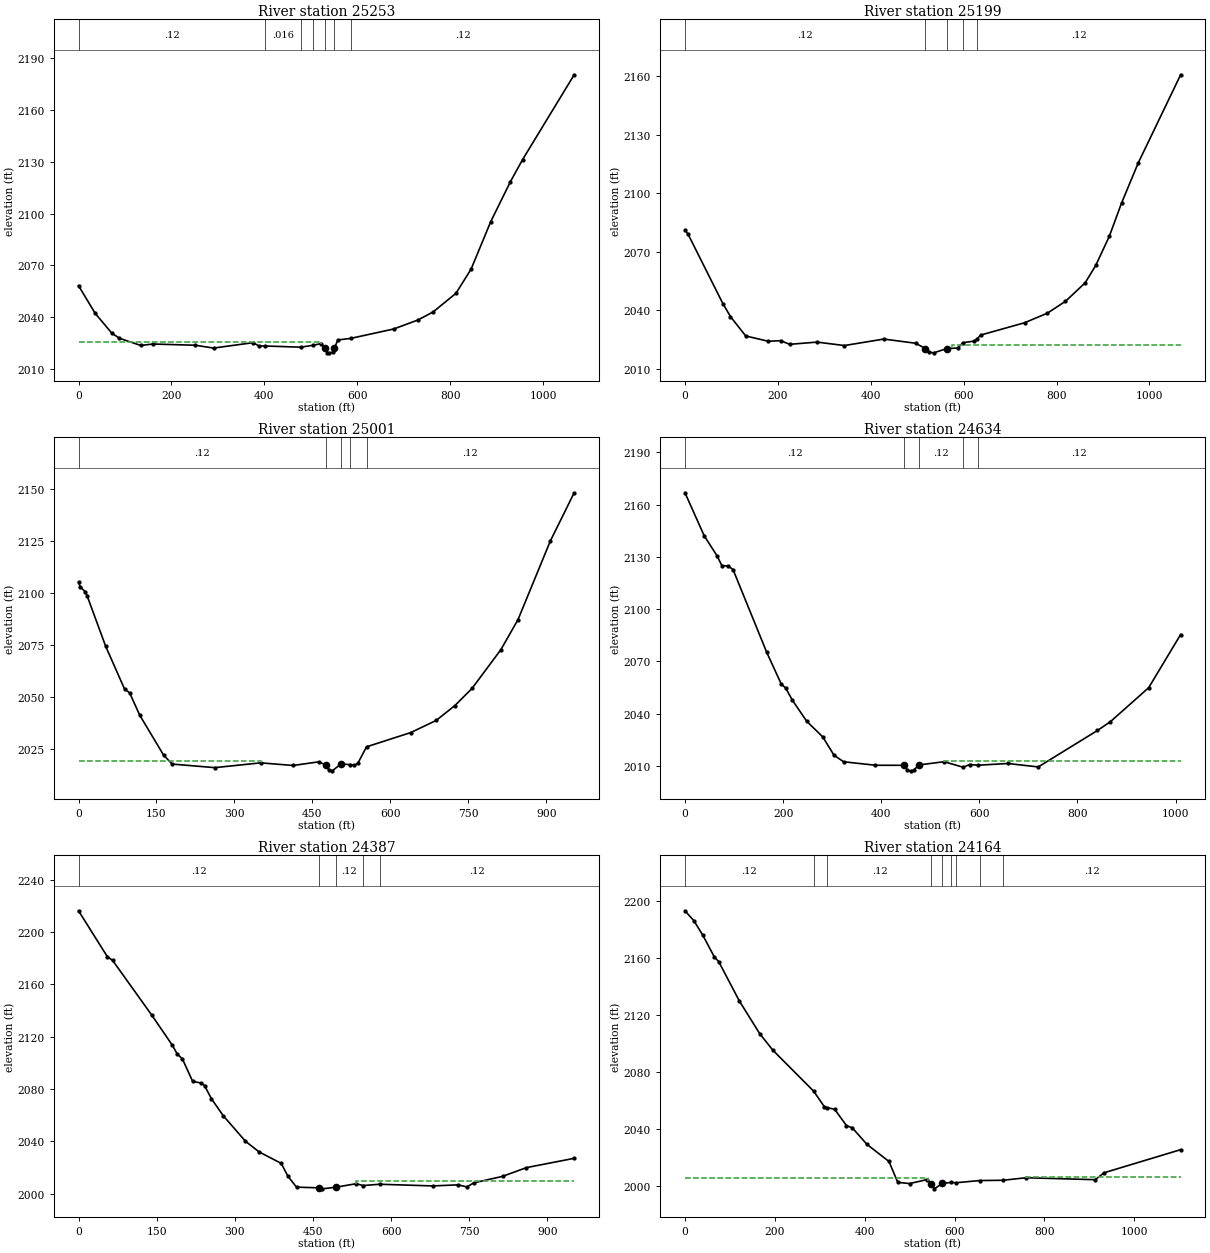
Type RM Length L Ch R = 1 ,25253   ,53.7,53.7,53.7
XS GIS Cut Line= 4
     2151753.671      262026.182     2152183.358        261912.9
     2152261.483      262032.692     2152726.327      261914.202
#Sta/Elev= 30
       0 2058.36    35.9 2042.36    71.9 2030.84    88.2 2027.97     134 2023.81
   160.1 2024.65   251.6 2023.93   290.8 2022.31   375.8 2025.42   388.8 2023.48
  402.432023.497  478.272022.829  505.642023.932   522.4 2024.92   531.12022.197
   535.4 2019.69   538.6 2019.55   548.4 2019.82  551.022022.203   558.1 2026.98
   586.42027.917   678.8 2033.34     731 2038.55   763.6 2043.21   812.6 2053.94
   845.2 2067.91   887.6  2095.4     930  2118.5   956.1 2131.19  1067.1 2180.16
#Mann= 7 ,-1 , 0
       0     .12       0  402.43    .016       0  478.27     .12       0
  505.64    .016       0   531.1     .04       0  551.02    .016       0
   586.4     .12       0
#XS Ineff= 2 , 0
          522.49 2026.05
Permanent Ineff=
       F       F
Bank Sta=531.1,551.02
XS Rating Curve= 0 ,0
Exp/Cntr=0.5,0.3

Type RM Length L Ch R = 1 ,25199   ,198.5,198.5,198.5
XS GIS Cut Line= 4
     2151712.659      262061.359     2152142.346      261948.078
     2152220.471       262067.87     2152685.315       261949.38
#Sta/Elev= 30
       0 2080.95     6.5 2078.97    81.7 2043.25      98 2036.63   130.7 2026.72
   179.7 2023.98   205.8 2024.31   225.4 2022.43   284.3 2023.57   343.1  2021.8
     428 2025.12   496.4 2022.99  517.712020.269   525.6 2018.32   535.4 2018.06
  564.33 2020.27   587.4 2020.53  598.672023.279   623.3 2024.09  629.152025.237
   636.3 2027.15     731 2033.48   779.9 2038.35   819.1 2044.47   861.5 2053.94
   884.4 2062.91   913.7  2077.9   939.8  2094.8   975.7 2115.37  1067.1 2160.64
#Mann= 5 ,-1 , 0
       0     .12       0  517.71     .04       0  564.33     .12       0
  598.67    .016       0  629.15     .12       0
#XS Ineff= 2 , 0
                          574.37         2022.06
Permanent Ineff=
       F       F
Bank Sta=517.71,564.33
XS Rating Curve= 0 ,0
Exp/Cntr=0.5,0.3

Type RM Length L Ch R = 1 ,25001   ,367.1,367.1,367.1
XS GIS Cut Line= 2
     2151797.985       262355.63     2152696.422      262035.318
#Sta/Elev= 30
       0 2105.05     3.3 2102.97    13.1 2100.46    16.4 2098.73    52.4 2074.25
    88.5 2053.82    98.3 2051.94     118 2041.08   163.9  2021.9   180.3 2017.65
   262.2 2015.94   350.7 2018.24     413 2016.98   462.2 2018.73   475.3 2017.25
   481.8 2014.89   488.4  2014.4   504.8 2017.69  522.852017.415     531 2016.98
   537.6 2018.05  554.212025.953   639.2  2032.8   688.3 2038.65   724.4 2045.83
   757.2 2054.04   812.9 2072.75   845.7 2087.14   907.9 2124.96   953.8 2148.18
#Mann= 5 ,-1 , 0
       0     .12       0   475.3     .04       0   504.8     .12       0
  522.85    .016       0  554.21     .12       0
#XS Ineff= 2 , 0
          350.78 2019.04
Permanent Ineff=
       F       F
Bank Sta=475.3,504.8
XS Rating Curve= 0 ,0
Exp/Cntr=0.3,0.1

Type RM Length L Ch R = 1 ,24634   ,246.3,246.3,246.3
XS GIS Cut Line= 4
     2151805.312      262619.988     2152093.412      262504.748
     2152407.341      262534.551     2152739.153      262339.835
#Sta/Elev= 30
       0 2166.86    39.2 2142.16    65.3 2130.68    75.1 2125.06    88.2 2124.76
      98 2122.75   166.6 2075.26     196  2057.2   205.8 2054.51   218.8 2047.79
   248.2 2035.64   280.9 2026.66   303.8 2016.15   323.3 2012.39   388.3 2010.39
   446.8 2010.35   453.3 2007.62   459.8 2007.18   466.3 2007.46   476.1 2010.53
   528.1 2012.42  567.562009.223   580.1  2010.8  597.232010.406   658.2  2011.4
   720.2 2009.42   840.8 2030.35   866.9 2035.32   945.2 2054.91  1010.4 2085.44
#Mann= 5 ,-1 , 0
       0     .12       0   446.8     .04       0   476.1     .12       0
  567.56    .016       0  597.23     .12       0
#XS Ineff= 2 , 0
                          527.84         2013.02
Permanent Ineff=
       F       F
Bank Sta=446.8,476.1
XS Rating Curve= 0 ,0
Exp/Cntr=0.3,0.1

Type RM Length L Ch R = 1 ,24387   ,223.4,223.4,223.4
XS GIS Cut Line= 2
     2151835.745      262916.828     2152730.276      262592.609
#Sta/Elev= 30
       0 2216.33    55.6 2181.06    65.4  2178.4   140.6  2136.5   179.8 2113.65
   189.6  2106.7   199.4 2103.01   219.1 2085.83   235.4 2084.54     242 2082.56
     255 2072.61   277.9 2059.52   320.4 2040.03   346.6 2031.85   389.1 2023.08
   402.2 2013.12   418.5 2004.88     461 2004.38   467.6 2003.59   493.7 2004.81
     533 2007.52  546.472006.104  577.892007.101   680.1 2005.82   729.1 2006.64
   745.5 2005.05   758.6 2008.14   814.2 2013.15   859.9 2019.83   951.5 2026.94
#Mann= 5 ,-1 , 0
       0     .12       0     461     .04       0   493.7     .12       0
  546.47    .016       0  577.89     .12       0
#XS Ineff= 2 , 0
                          532.29         2009.24
Permanent Ineff=
       F       F
Bank Sta=461,493.7
XS Rating Curve= 0 ,0
Exp/Cntr=0.5,0.3

Type RM Length L Ch R = 1 ,24164   ,34.3,34.3,34.3
XS GIS Cut Line= 4
     2151894.339      263097.818      2152407.36      262967.609
     2152353.974      262840.005     2152736.787      262631.672
#Sta/Elev= 30
       0 2193.41    19.6 2186.51    39.2 2176.55    65.3 2160.99    75.2 2157.62
   120.9 2130.11   166.6 2106.93     196 2095.31  286.742066.541   310.4 2055.63
  317.212054.972   333.2 2053.95   359.4 2042.48   372.5 2040.86   405.1 2029.26
   454.1 2017.25   473.7 2002.59   499.9 2001.71   538.9 2004.52   548.6 2001.56
     555 1998.01  572.992001.813  592.372002.523  602.682002.279  656.412003.844
  707.782004.023   759.4 2005.81   913.4 2004.44     933 2009.31  1103.4 2025.54
#Mann= 9 ,-1 , 0
       0     .12       0  286.74     .06       0  317.21     .12       0
   548.6     .04       0  572.99     .12       0  592.37    .016       0
  602.68     .12       0  656.41    .016       0  707.78     .12       0
#XS Ineff= 2 , 0
           541.2 2005.87  759.02         2006.67
Permanent Ineff=
       F       F
Bank Sta=548.6,572.99
XS Rating Curve= 0 ,0
Exp/Cntr=0.5,0.3

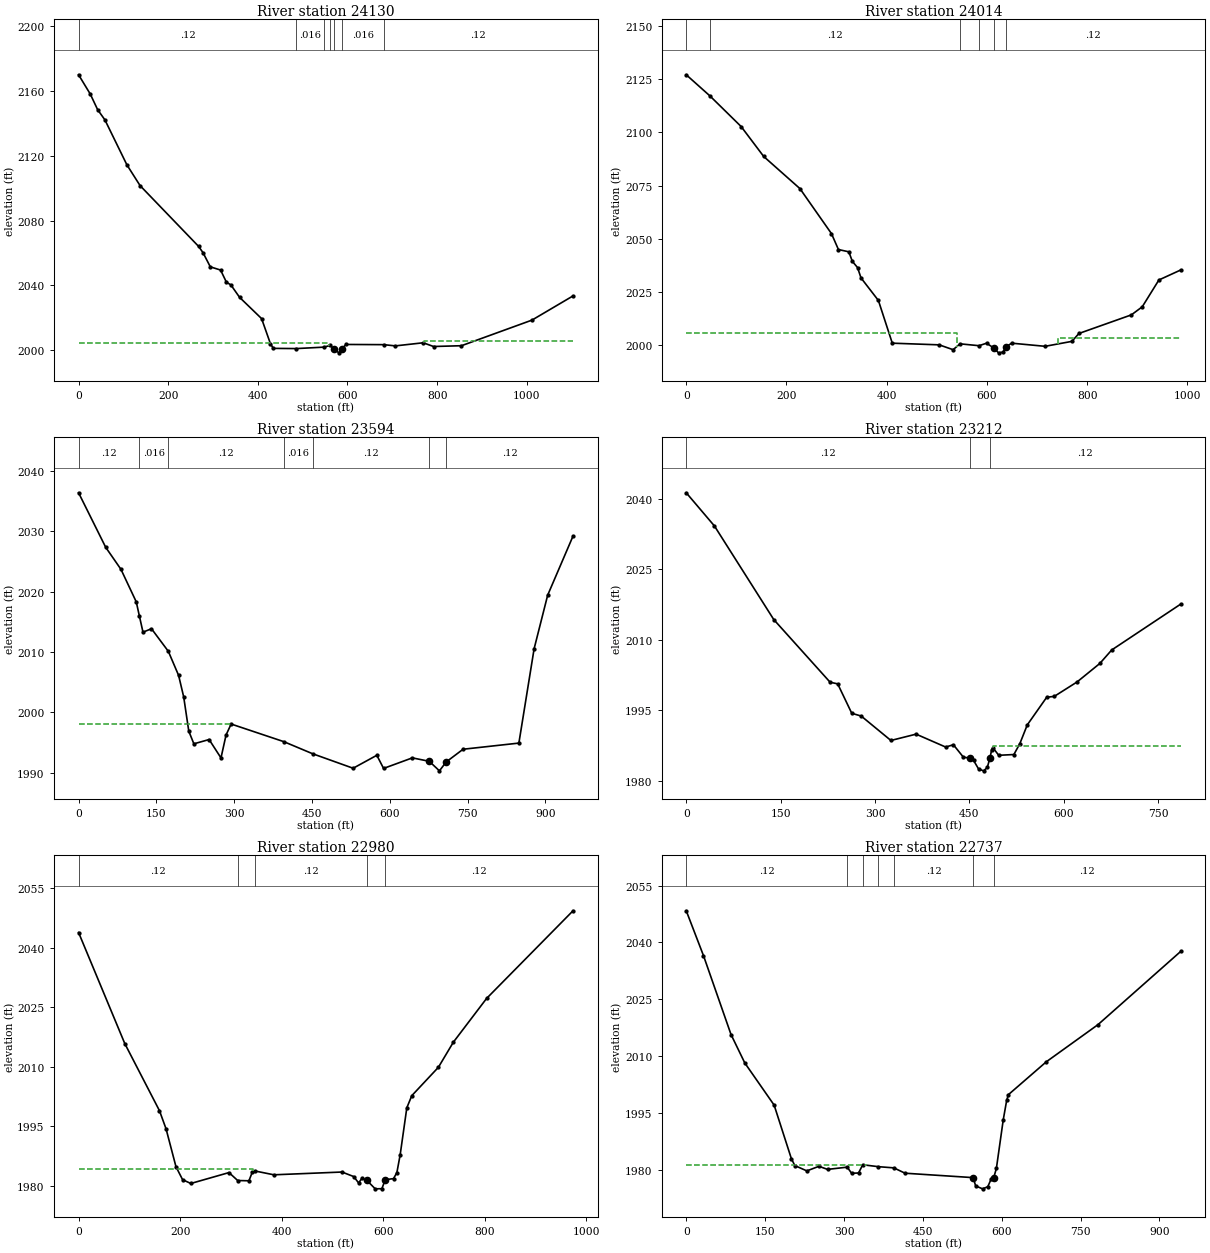
Type RM Length L Ch R = 1 ,24130   ,114.9,114.9,114.9
XS GIS Cut Line= 4
     2151937.308      263116.047     2152450.329      262985.838
     2152396.943      262858.234     2152779.756      262649.901
#Sta/Elev= 30
       0 2169.99    26.1 2158.09    42.5 2148.48    58.8 2142.15   107.8 2114.44
   137.2 2101.62   267.9 2064.09   277.7 2060.22     294 2051.49   316.9 2049.51
     330 2041.96   339.8 2040.37   359.4 2032.64   408.4 2019.56     428 2004.18
   434.5 2001.18   486.22001.061  548.092001.957  560.972002.993   571.1 2000.72
   580.8 1998.43   587.8 2000.96   596.8  2003.6  680.85 2003.48   706.9 2002.72
   769.2 2004.64   792.1 2002.34   854.4 2002.82  1011.7 2018.61  1103.4 2033.55
#Mann= 7 ,-1 , 0
       0     .12       0   486.2    .016       0  548.09     .12       0
  560.97    .016       0   571.1     .04       0   587.8    .016       0
  680.85     .12       0
#XS Ineff= 2 , 0
          559.28 2004.52  771.05         2005.72
Permanent Ineff=
       F       F
Bank Sta=571.1,587.8
XS Rating Curve= 0 ,0
Exp/Cntr=0.5,0.3

Type RM Length L Ch R = 1 ,24014   ,420.7,420.7,420.7
XS GIS Cut Line= 3
 2151968.4154592 263176.094245262152500.95048019262993.895452907
     2152778.454      262673.338
#Sta/Elev= 30
       02127.039  47.1332117.142 109.5482102.738 154.6272088.672 226.8722073.601
 289.8612052.453 303.7312044.984 324.5362043.918 331.4712039.447 341.8742036.523
 348.8092031.657 383.4842021.077 411.225 2001.02 504.8482000.236 532.589 1997.96
 546.459 2000.71 584.2731999.836 599.3112001.003   614.41998.669 623.2231996.484
 632.5271996.826  637.311999.161 649.4372001.023  716.261999.548 769.7412001.874
 783.7112005.573 888.3762014.307 910.0962018.097 943.344  2030.7 986.8282035.383
#Mann= 6 ,-1 , 0
       0     .12       0  47.133     .12       0 546.459    .016       0
 584.273     .12       0   614.4     .04       0  637.31     .12       0
#XS Ineff= 2 , 0
          540.02 2005.95  741.65         2003.41
Permanent Ineff=
       F       F
Bank Sta=614.4,637.31
XS Rating Curve= 0 ,0
Exp/Cntr=0.3,0.1

Type RM Length L Ch R = 1 ,23594   ,382.1,382.1,382.1
XS GIS Cut Line= 3
     2152375.759      263825.118     2152615.165      263442.737
     2152960.084      263077.614
#Sta/Elev= 30
       0  2036.4    52.3 2027.36    81.7 2023.71   111.2 2018.32  117.382015.918
   124.2 2013.29   140.6 2013.86  173.052010.117   192.9 2006.12   202.7 2002.55
   212.5 1996.88   222.3 1994.78   251.7 1995.49   274.6 1992.44   284.4 1996.25
   294.2 1998.06  395.711995.139  451.331993.133   529.4 1990.73   575.1 1992.88
   588.1  1990.7   643.6 1992.45   676.2 1991.88   695.8  1990.3   708.8 1991.77
   741.4 1993.88     849  1994.9   878.4 2010.55   904.5 2019.42   953.4 2029.22
#Mann= 7 ,-1 , 0
       0     .12       0  117.38    .016       0  173.05     .12       0
  395.71    .016       0  451.33     .12       0   676.2     .04       0
   708.8     .12       0
#XS Ineff= 2 , 0
          293.99 1998.04
Permanent Ineff=
       F       F
Bank Sta=676.2,708.8
XS Rating Curve= 0 ,0
Exp/Cntr=0.3,0.1

Type RM Length L Ch R = 1 ,23212   ,231.4,231.4,231.4
XS GIS Cut Line= 3
     2152432.264      263883.441     2152820.299      263613.238
2153076.16583639263432.807587767
#Sta/Elev= 30
       02041.334  44.851 2034.25 139.1222014.307 228.679 2000.95 240.7182000.601
 263.0631994.336 278.1721993.734 325.3071988.535 365.3721989.884 412.3371987.132
 424.6211987.624 440.6121984.956  450.331984.796 456.6041984.311 464.5991982.468
 472.5951982.062 478.4921982.781  482.741984.804 485.555 1986.61 487.9091986.913
 496.6811985.375 520.7681985.537 530.2871987.865 542.0591991.852 572.957 1997.75
 585.0011997.935 621.132    2001  657.422004.953 676.2552007.822  785.932017.599
#Mann= 3 ,-1 , 0
       0     .12       0  450.33     .04       0  482.74     .12       0
#XS Ineff= 2 , 0
                           488.2         1987.32
Permanent Ineff=
       F       F
Bank Sta=450.33,482.74
XS Rating Curve= 0 ,0
Exp/Cntr=0.3,0.1

Type RM Length L Ch R = 1 ,22980   ,243.8,243.8,243.8
XS GIS Cut Line= 3
     2152460.987      263955.181     2152701.402      263947.233
     2153321.313      263555.815
#Sta/Elev= 30
       0 2043.83      91 2015.82   159.3 1998.89   172.3  1994.3   191.8 1984.76
   204.8  1981.5     221 1980.53   296.2 1983.28  313.33 1981.28   335.5 1981.21
     342 1983.36  348.261983.662   384.6 1982.72   518.8 1983.42   541.7 1982.28
   551.5 1980.67     558 1981.84   567.8  1981.3   584.2 1979.18   597.3 1979.22
  603.911981.484   620.2 1981.76   626.8 1983.26   633.3 1987.76   646.4 1999.62
   656.2 2002.68   708.6 2009.84     738 2016.16   803.5  2027.2   973.7 2049.31
#Mann= 5 ,-1 , 0
       0     .12       0  313.33    .016       0  348.26     .12       0
   567.8     .04       0  603.91     .12       0
#XS Ineff= 2 , 0
           344.1 1984.15
Permanent Ineff=
       F       F
Bank Sta=567.8,603.91
XS Rating Curve= 0 ,0
Exp/Cntr=0.3,0.1

Type RM Length L Ch R = 1 ,22737   ,249.3,249.3,249.3
XS GIS Cut Line= 2
     2152457.013       263975.05     2153396.815      264014.788
#Sta/Elev= 30
       0 2048.37    32.8 2036.52    85.2 2015.67   111.4 2008.16   167.2 1997.03
   199.9 1982.92   206.5 1981.06   229.4 1979.65   252.4 1980.86   268.8 1980.05
   306.21980.637   314.6 1979.02   327.8  1979.1  335.761981.275  365.321980.768
  394.89 1980.45   416.2 1979.04  545.751977.873   550.6 1975.68   563.7 1974.91
   573.6 1975.47   580.1 1977.51  584.951977.872     590 1980.32   603.1  1993.2
   609.6 1998.31   612.9  1999.8     685 2008.48   783.3 2018.29   940.6 2037.63
#Mann= 7 ,-1 , 0
       0     .12       0   306.2    .016       0  335.76     .12       0
  365.32     .06       0  394.89     .12       0  545.75     .04       0
  584.95     .12       0
#XS Ineff= 2 , 0
          342.98 1981.32
Permanent Ineff=
       F       F
Bank Sta=545.75,584.95
XS Rating Curve= 0 ,0
Exp/Cntr=0.3,0.1

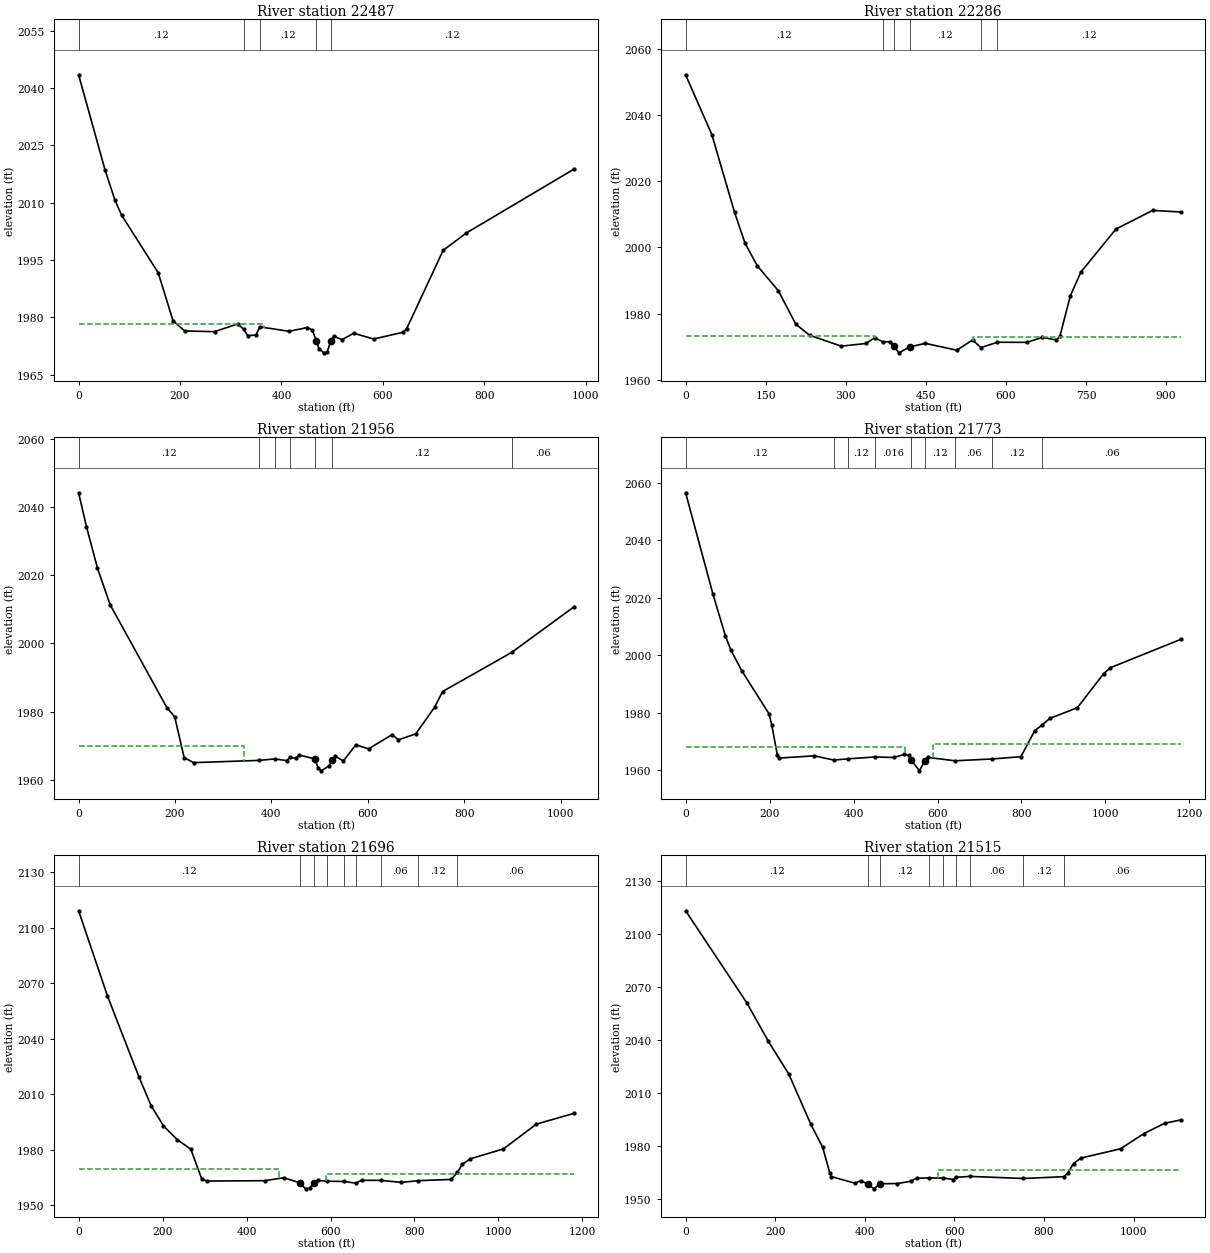
Type RM Length L Ch R = 1 ,22487   ,201.2,201.2,201.2
XS GIS Cut Line= 3
     2152462.974      264030.683     2153074.938      264286.992
      2153386.88      264310.835
#Sta/Elev= 30
       0  2043.5    52.3 2018.51    71.9 2010.59      85  2006.7   156.9  1991.7
   186.3 1979.08   209.2 1976.44     268 1976.25   313.8 1978.28   325.2 1976.93
   333.4 1975.22   349.7 1975.35  357.221977.519   415.1 1976.35     451 1977.34
   460.8 1976.69  468.811973.902   473.9 1971.83   483.7 1970.71   490.2 1970.96
  497.491973.903   503.3 1975.05   519.7 1974.17   542.5 1975.84   581.8 1974.33
   640.6 1976.12   647.1 1977.08   718.9 1997.53   764.5 2002.07   976.3 2018.75
#Mann= 5 ,-1 , 0
       0     .12       0   325.2    .016       0  357.22     .12       0
  468.81     .04       0  497.49     .12       0
#XS Ineff= 2 , 0
          366.37 1978.36
Permanent Ineff=
       F       F
Bank Sta=468.81,497.49
XS Rating Curve= 0 ,0
Exp/Cntr=0.3,0.1

Type RM Length L Ch R = 1 ,22286   ,330.3,330.3,330.3
XS GIS Cut Line= 2
     2152405.354      264279.045     2153301.444      264517.472
#Sta/Elev= 30
       0 2052.09    49.2 2034.03    91.7  2010.6   111.4 2001.26   134.3 1994.47
   173.7 1986.96   206.4 1976.86   232.6 1973.49   291.6 1970.23   337.5 1971.04
   353.9 1972.72  369.991971.533   383.4 1971.58   389.9 1970.16   399.7 1968.22
   419.4    1970   448.9 1971.08   507.9 1969.02   537.4 1972.08  553.381969.817
  583.941971.414   638.9 1971.38   668.4 1972.87   694.6 1972.11   701.2 1973.31
   720.8 1985.48   740.5  1992.6     806 2005.55   874.8 2011.18   927.3  2010.7
#Mann= 6 ,-1 , 0
       0     .12       0  369.99    .016       0   389.9     .04       0
   419.4     .12       0  553.38     .06       0  583.94     .12       0
#XS Ineff= 2 , 0
          355.23 1973.34  538.98         1973.02
Permanent Ineff=
       F       F
Bank Sta=389.9,419.4
XS Rating Curve= 0 ,0
Exp/Cntr=0.3,0.1

Type RM Length L Ch R = 1 ,21956   ,183.2,183.2,183.2
XS GIS Cut Line= 3
      2152353.54      264470.648     2152985.051      264713.703
     2153334.443      264741.915
#Sta/Elev= 30
       0 2044.11    16.3 2034.19    39.2    2022    65.4 2011.32   183.1 1981.21
   199.4 1978.48     219 1966.54   238.6 1965.07  375.331965.735  406.971966.155
   431.5 1965.67  438.621966.589   451.1 1966.36   457.6  1967.3   490.3 1966.17
   496.9 1963.46   503.4 1962.67   519.8 1964.15   526.3 1965.83   532.8 1966.95
   549.2 1965.56   575.3 1970.29   601.5 1969.11   650.5 1973.27   663.6 1971.74
   699.6 1973.51   738.9 1981.37   755.3  1985.9  898.271997.331  1027.2 2010.63
#Mann= 7 ,-1 , 0
       0     .12       0  375.33     .06       0  406.97    .016       0
  438.62     .12       0   490.3     .04       0   526.3     .12       0
  898.27     .06       0
#XS Ineff= 2 , 0
          343.43 1969.81
Permanent Ineff=
       F       F
Bank Sta=490.3,526.3
XS Rating Curve= 0 ,0
Exp/Cntr=0.5,0.3

Type RM Length L Ch R = 1 ,21773   ,76.4,76.4,76.4
XS GIS Cut Line= 4
     2152323.345      264535.836     2152762.055       264736.54
     2152742.668      264874.138       2153297.1      264934.663
#Sta/Elev= 30
       0 2056.53    65.2 2021.24    94.5 2006.87   107.6 2001.88   133.6 1994.63
   198.8  1979.6   205.4 1975.61   218.4 1965.34   221.7 1964.21   306.4    1965
  353.431963.516  385.911963.956  450.871964.601   495.4 1964.43   521.2  1965.5
   530.9 1965.12   537.4 1963.59   556.8 1959.78   569.7 1963.25   576.2 1964.47
  641.721963.276  730.86 1963.92   798.6 1964.71   831.4 1973.72  849.711975.799
   867.4 1978.01   933.1 1981.76   995.4 1993.54  1011.8 1995.66  1179.1 2005.52
#Mann= 9 ,-1 , 0
       0     .12       0  353.43     .06       0  385.91     .12       0
  450.87    .016       0   537.4     .04       0   569.7     .12       0
  641.72     .06       0  730.86     .12       0  849.71     .06       0
#XS Ineff= 2 , 0
          521.74 1968.12  588.26         1969.12
Permanent Ineff=
       F       F
Bank Sta=537.4,569.7
XS Rating Curve= 0 ,0
Exp/Cntr=0.5,0.3

Type RM Length L Ch R = 1 ,21696   ,181.6,181.6,181.6
XS GIS Cut Line= 4
     2152245.484      264549.167     2152684.194      264749.871
     2152664.807      264887.469     2153219.239      264947.993
#Sta/Elev= 30
       0 2109.22    68.4 2063.34   143.4 2019.47   172.8 2003.74   202.1 1992.88
   234.7 1985.46   267.3 1980.18   293.4 1964.03   306.4 1962.98   443.3  1963.2
   488.9 1964.78  526.521962.074   540.6 1958.78   550.3 1959.15     560 1961.99
   569.7 1963.32  592.521962.903  630.911962.775  660.62 1961.86   673.9 1963.41
  720.041963.351     769 1962.27  809.181963.201   887.1 1963.86   902.41967.691
   913.4 1971.97   933.1 1975.05  1011.8 1980.37  1090.5 1993.82  1179.1 1999.57
#Mann= 9 ,-1 , 0
       0     .12       0  526.52     .04       0     560     .12       0
  592.52     .08       0  630.91    .016       0  660.62     .08       0
  720.04     .06       0  809.18     .12       0   902.4     .06       0
#XS Ineff= 2 , 0
          477.39 1969.37  588.26         1966.74
Permanent Ineff=
       F       F
Bank Sta=526.52,560
XS Rating Curve= 0 ,0
Exp/Cntr=0.5,0.3

Type RM Length L Ch R = 1 ,21515   ,359,359,359
XS GIS Cut Line= 3
     2152175.589      265015.352     2152331.839      264850.422
     2153197.724      264995.821
#Sta/Elev= 30
       0 2113.14   136.3 2061.24     185 2039.23   230.5 2020.73   279.6 1992.39
   305.8 1979.49   322.2 1964.71   325.5 1962.84   377.9  1959.1     391 1960.52
   407.4 1958.53   420.5 1955.91   433.6 1958.77   472.9 1958.92   502.4 1960.17
   515.5 1961.94  544.461962.058  574.411962.038   597.4 1961.19  604.361962.434
  634.961962.955  754.111961.765  843.961962.775   852.9 1964.61     866 1970.23
   882.4  1973.3   970.9 1978.56  1023.3 1987.17  1069.2 1992.93  1105.2 1994.88
#Mann= 9 ,-1 , 0
       0     .12       0   407.4     .04       0   433.6     .12       0
  544.46     .08       0  574.41    .016       0  604.36     .08       0
  634.96     .06       0  754.11     .12       0  843.96     .06       0
#XS Ineff= 2 , 0
                          563.48         1966.36
Permanent Ineff=
       F       F
Bank Sta=407.4,433.6
XS Rating Curve= 0 ,0
Exp/Cntr=0.3,0.1