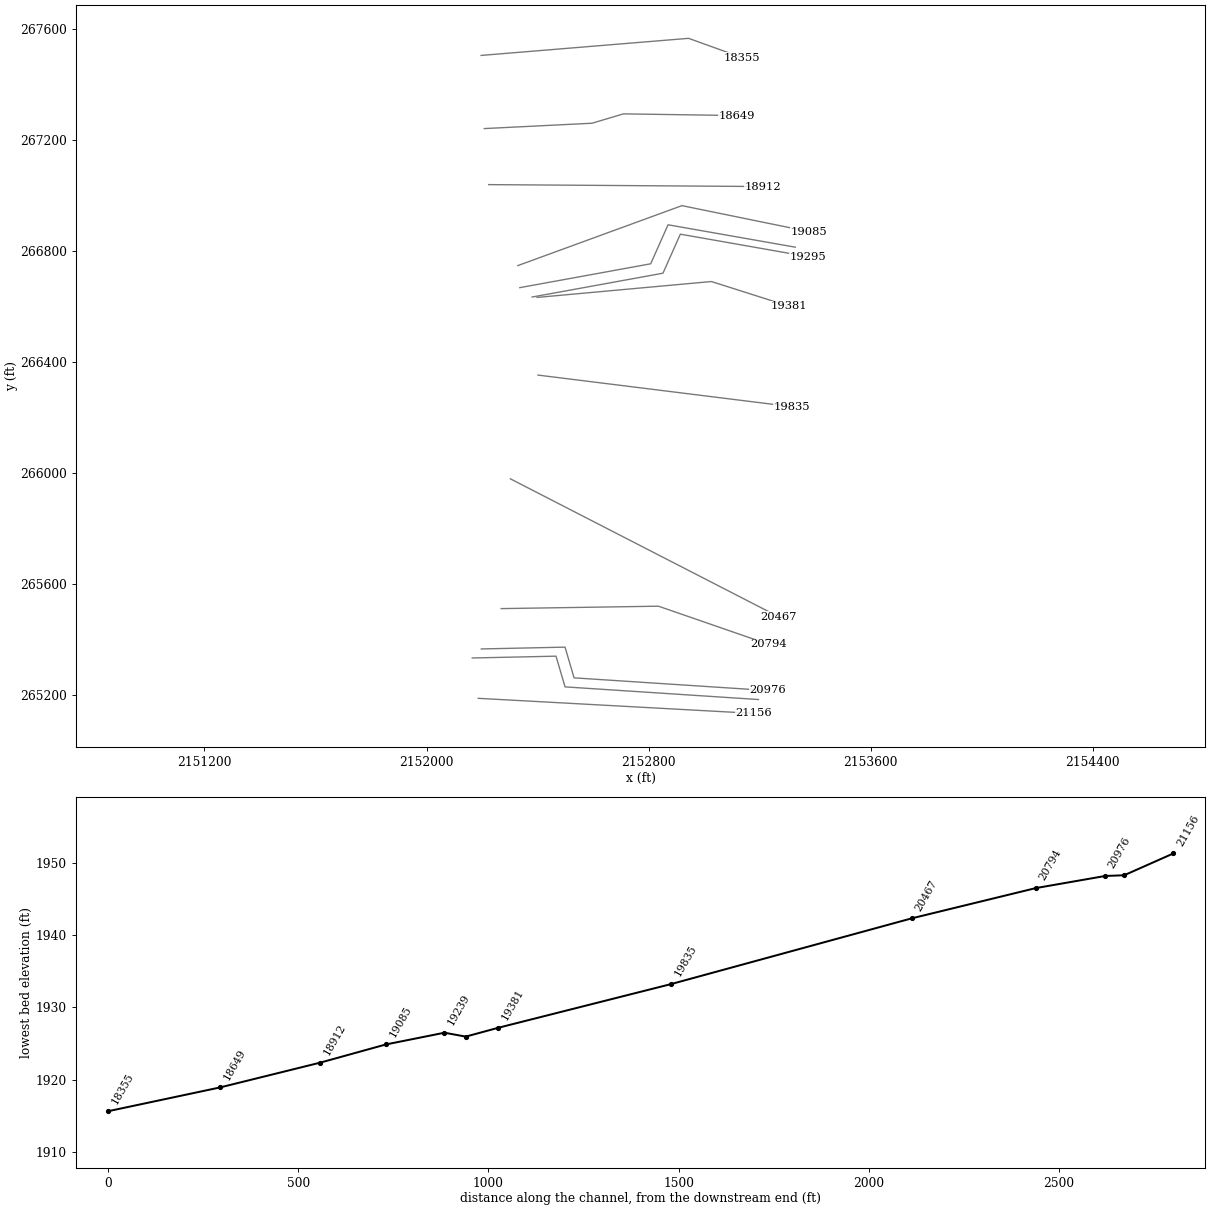
HEC-RAS study HARTSRN.prj: HARTSRN

--- HARTSRN.g01 (geometry) --- (continued)

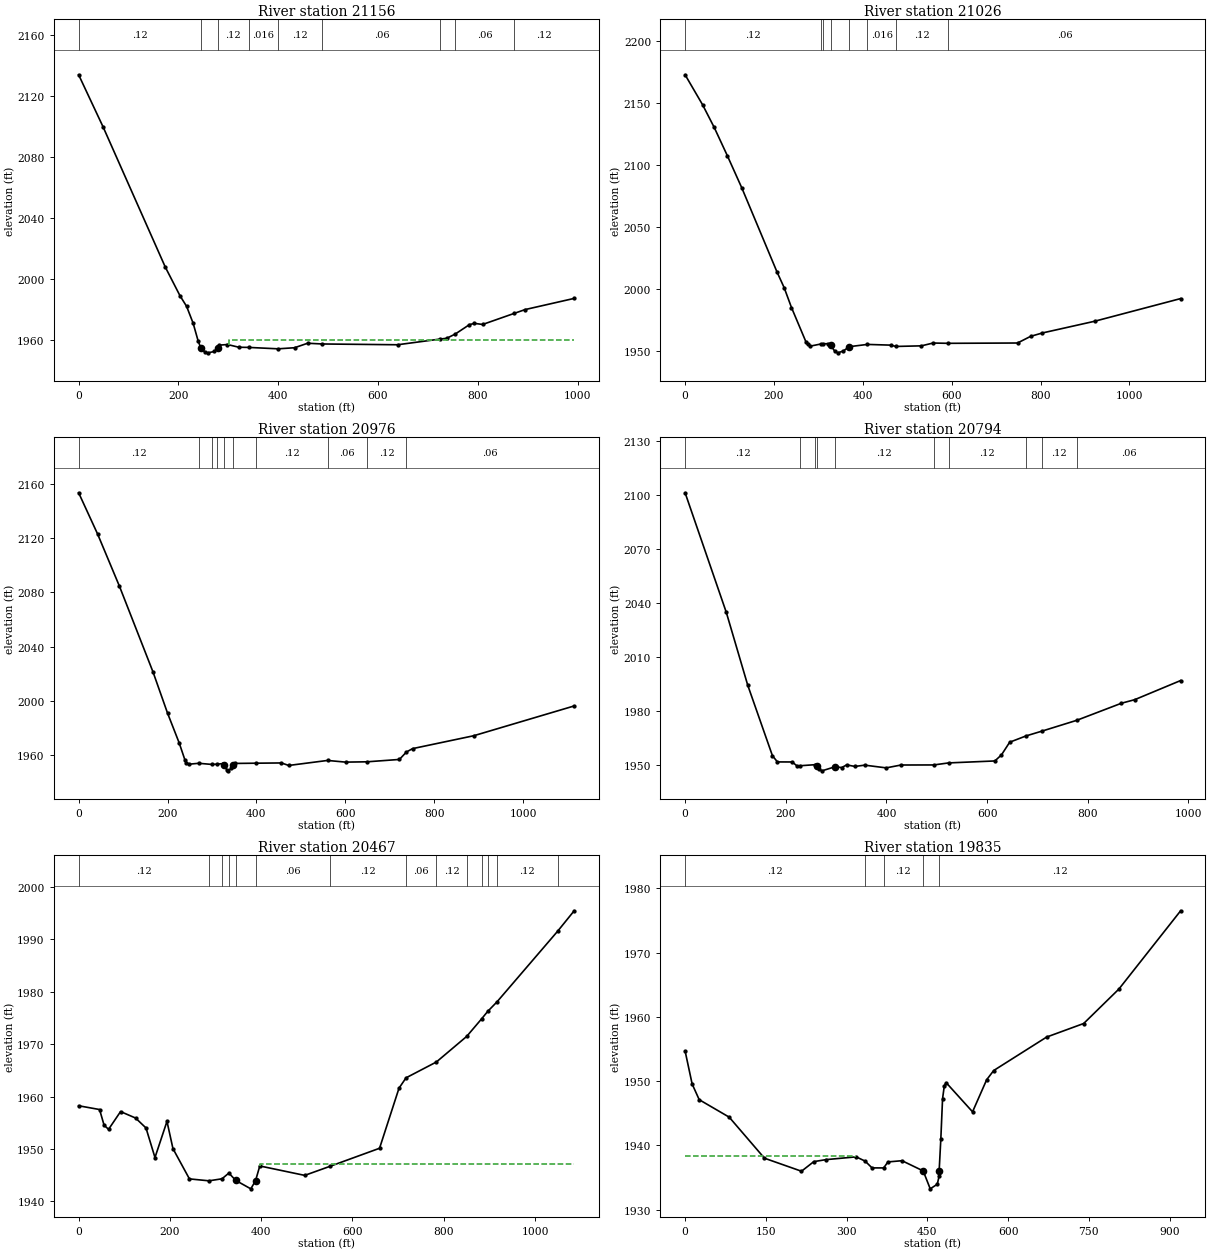
Type RM Length L Ch R = 1 ,21156   ,129.5,129.5,129.5
XS GIS Cut Line= 2
      2152186.44      265186.793     2153178.193       265132.54
#Sta/Elev= 30
       0 2134.13    49.2 2099.74   173.7 2007.73   203.2 1988.86   216.4 1981.93
   229.5 1970.83   239.3 1959.45  244.511954.813   252.4    1952     259 1951.37
   272.1 1952.27   278.6 1954.86   281.9 1956.42   298.3 1956.84   321.2 1955.04
  340.631954.942  399.791954.013   432.7 1954.72   458.9 1957.67  488.531957.197
   639.2 1956.68  725.181960.451   737.6 1960.93  754.761963.708   783.4 1969.93
   793.3 1970.74   809.7 1970.02  873.091977.309   894.9 1979.81   993.2 1987.15
#Mann= 9 ,-1 , 0
       0     .12       0  244.51     .04       0   278.6     .12       0
  340.63    .016       0  399.79     .12       0  488.53     .06       0
  725.18     .12       0  754.76     .06       0  873.09     .12       0
#XS Ineff= 2 , 0
                          301.09         1960.04
Permanent Ineff=
       F       F
Bank Sta=244.51,278.6
XS Rating Curve= 0 ,0
Exp/Cntr=0.5,0.3

Type RM Length L Ch R = 1 ,21026   ,49.8,49.8,49.8
XS GIS Cut Line= 4
     2152164.738      265332.193     2152466.388      265338.703
      2152498.94      265228.026     2153195.554      265182.453
#Sta/Elev= 30
       0 2172.88    39.4 2148.64    65.6 2130.31    95.1 2107.51   127.9 2081.31
   206.6 2013.84     223 2000.91   239.4 1984.94   272.2    1957   275.5 1955.08
     282 1953.78  305.561955.479  309.281955.601     321 1955.75   327.4 1954.42
     337 1949.59   343.4 1948.34   356.2 1949.83     369 1953.29  410.271955.138
     463 1954.56  474.361953.501   531.8 1953.99     558 1956.25  592.761956.026
   748.1 1956.28   777.6 1961.66   803.8 1964.37   921.8 1973.86  1115.2 1992.16
#Mann= 8 ,-1 , 0
       0     .12       0  305.56    .016       0  309.28     .12       0
   327.4     .04       0     369     .12       0  410.27    .016       0
  474.36     .12       0  592.76     .06       0
#XS Ineff= 2 , 0
          317.95  1954.2  395.05          1954.2
Permanent Ineff=
       F       F
Bank Sta=327.4,369
XS Rating Curve= 0 ,0
Exp/Cntr=0.5,0.3

Type RM Length L Ch R = 1 ,20976   ,182.5,182.5,182.5
XS GIS Cut Line= 4
      2152197.29      265364.745      2152498.94      265371.255
     2152531.492      265260.578     2153228.106      265215.005
#Sta/Elev= 30
       0 2153.53    42.6 2123.14    91.8 2084.57   167.3 2021.32     200 1990.92
   226.3 1968.85   239.4 1956.09   242.7 1954.08   249.2 1953.16  270.241953.813
  299.791952.973  312.431953.172   324.2 1953.59   327.4 1952.66   333.8  1948.7
     337 1948.24   343.4 1950.04   346.6 1952.77     353 1953.71  399.571953.882
   456.4 1954.07   472.8 1952.21  560.141955.914   600.6 1954.68  648.94 1954.91
   721.9 1956.65  737.741962.155   751.4 1964.63     889 1974.14  1115.2 1996.15
#Mann= 10 ,-1 , 0
       0     .12       0  270.24    .016       0  299.79     .12       0
  312.43    .016       0   327.4     .04       0   346.6    .016       0
  399.57     .12       0  560.14     .06       0  648.94     .12       0
  737.74     .06       0
#XS Ineff= 2 , 0
          323.04 1952.98   351.2         1953.07
Permanent Ineff=
       F       F
Bank Sta=327.4,346.6
XS Rating Curve= 0 ,0
Exp/Cntr=0.5,0.3

Type RM Length L Ch R = 1 ,20794   ,326.4,326.4,326.4
XS GIS Cut Line= 3
     2152268.905      265510.144     2152835.311      265518.825
     2153230.276      265382.106
#Sta/Elev= 30
       0  2101.2    81.9 2034.65   124.4 1994.21   173.5 1954.97   183.4 1951.52
   212.8 1951.49   222.7  1949.2  228.12 1949.39  257.661949.966     262 1949.18
   265.2 1947.54   271.8 1946.56     298 1948.83   311.1 1948.38   320.9 1949.87
   337.3 1949.01   356.9 1949.72   399.5 1948.21     429  1949.8  493.981949.835
  523.521950.969   615.4 1952.06   628.5 1955.44   644.8 1962.48  677.31 1965.98
  708.571968.622     7781974.656   866.9 1984.17     893 1986.12   984.4 1996.78
#Mann= 10 ,-1 , 0
       0     .12       0  228.12    .016       0  257.66     .12       0
     262     .04       0     298     .12       0  493.98     .06       0
  523.52     .12       0  677.31     .06       0  708.57     .12       0
     778     .06       0
Bank Sta=262,298
XS Rating Curve= 0 ,0
Exp/Cntr=0.3,0.1

Type RM Length L Ch R = 1 ,20467   ,632.8,632.8,632.8
XS GIS Cut Line= 2
     2152302.036       265977.84     2153267.667      265481.116
#Sta/Elev= 30
       0 1958.23    45.9 1957.51    55.8 1954.51    65.6 1953.73    91.9 1957.12
   124.7 1955.89   147.6 1953.99   167.3 1948.34   193.6 1955.25   206.7 1950.04
   242.8 1944.26  285.651943.892   314.2 1944.28   329.2 1945.37   344.5 1943.96
   377.3 1942.36  387.63 1943.91     397 1946.73   495.4 1944.93  551.38 1946.68
   659.4 1950.11   702.1  1961.6  717.471963.567   783.91966.588  850.331971.477
  883.551974.884  896.43 1976.26  916.771978.078 1049.641991.573  1085.9 1995.48
#Mann= 14 ,-1 , 0
       0     .12       0  285.65    .016       0   314.2     .04       0
   329.2     .12       0   344.5     .04       0  387.63     .06       0
  551.38     .12       0  717.47     .06       0   783.9     .12       0
  850.33     .06       0  883.55     .12       0  896.43     .06       0
  916.77     .12       0 1049.64     .06       0
#XS Ineff= 2 , 0
                          396.88         1947.04
Permanent Ineff=
       F       F
Bank Sta=344.5,387.63
XS Rating Curve= 0 ,0
Exp/Cntr=0.3,0.1

Type RM Length L Ch R = 1 ,19835   ,453.6,453.6,453.6
XS GIS Cut Line= 2
     2152401.397      266351.752     2153314.758      266238.046
#Sta/Elev= 30
       0  1954.7    13.1 1949.56    26.2 1947.12    81.9  1944.4   147.4 1938.01
   216.2 1935.98   239.1 1937.48     262 1937.79   317.7 1938.22   334.41937.556
   347.2  1936.5  368.851936.496   376.7 1937.43   402.9 1937.62   442.2 1936.03
   455.3 1933.24   468.4 1933.96   471.7 1935.19  471.84 1935.99     475 1941.02
   478.2 1947.27   481.5  1949.3   484.8 1949.78   533.9 1945.23   560.1 1950.22
   573.2 1951.66   671.5 1956.87   740.3 1958.98   805.8 1964.35   920.4 1976.53
#Mann= 5 ,-1 , 0
       0     .12       0   334.4    .016       0  368.85     .12       0
   442.2     .04       0  471.84     .12       0
#XS Ineff= 2 , 0
          315.14 1938.28
Permanent Ineff=
       F       F
Bank Sta=442.2,471.84
XS Rating Curve= 0 ,0
Exp/Cntr=0.3,0.1

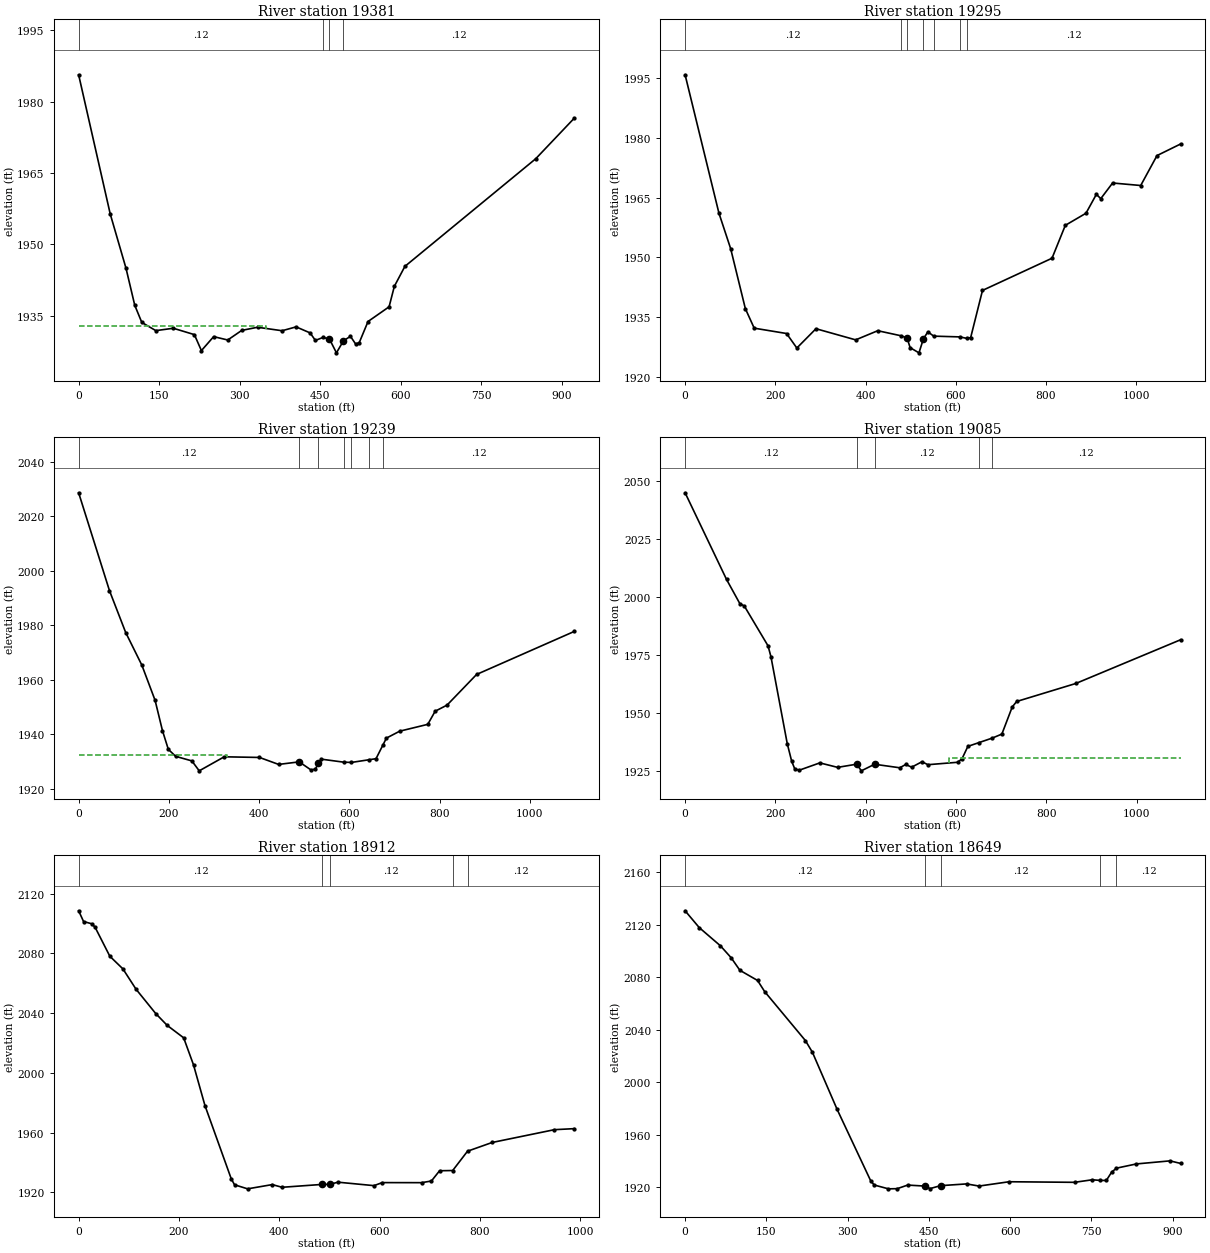
Type RM Length L Ch R = 1 ,19381   ,85.7,85.7,85.7
XS GIS Cut Line= 3
      2152398.35      266631.613     2153025.954      266688.905
       2153304.6      266600.363
#Sta/Elev= 30
       0 1985.67    58.8 1956.41    88.2 1944.98   104.5 1937.19   117.6 1933.59
   143.7 1931.86   176.3 1932.36   215.5 1931.02   228.6 1927.66   251.4  1930.6
   277.6 1929.89   303.7 1931.91   333.1 1932.57   378.8 1931.84   404.9 1932.65
     431 1931.38   440.8  1929.8  454.891930.429     467 1930.09     480 1927.19
   493.1 1929.73   506.1 1930.66   515.9 1929.02   522.5 1929.35   538.8 1933.78
     578 1936.87   587.8 1941.18   607.4 1945.37   851.1 1968.02   922.6 1976.52
#Mann= 4 ,-1 , 0
       0     .12       0  454.89    .016       0     467     .04       0
   493.1     .12       0
#XS Ineff= 2 , 0
          349.67 1932.83
Permanent Ineff=
       F       F
Bank Sta=467,493.1
XS Rating Curve= 0 ,0
Exp/Cntr=0.5,0.3

Type RM Length L Ch R = 1 ,19295   ,56,56,56
XS GIS Cut Line= 4
     2152380.301      266633.009     2152851.655      266718.947
     2152914.155      266859.572     2153372.489      266778.843
#Sta/Elev= 30
       0 1995.85      75 1961.07     101 1952.14   133.6 1937.05   153.2 1932.16
   224.9 1930.82   247.7 1927.17   290.1 1932.02   378.1 1929.22     427 1931.52
  478.821930.245   492.2 1929.66   498.8 1927.26   518.4 1925.96   528.2 1929.47
   538.1 1931.24   551.11930.157  609.251929.966  623.821929.605     633  1929.8
   659.2 1941.65   813.3 1949.74   842.8 1958.01   888.6 1961.05   911.6  1965.8
   921.4 1964.72   947.6 1968.65  1009.9 1968.02    1046 1975.54  1098.4 1978.46
#Mann= 7 ,-1 , 0
       0     .12       0  478.82    .016       0   492.2     .04       0
   528.2    .016       0   551.1     .12       0  609.25    .016       0
  623.82     .12       0
#XS Ineff= 2 , 0
          291.31 1931.96
Permanent Ineff=
       F       F
Bank Sta=492.2,528.2
XS Rating Curve= 0 ,0
Exp/Cntr=0.5,0.3

Type RM Length L Ch R = 1 ,19239   ,154.1,154.1,154.1
XS GIS Cut Line= 4
      2152336.03      266666.863     2152807.385      266752.801
     2152869.885      266893.426     2153328.218      266812.697
#Sta/Elev= 30
       0 2028.71    68.4 1992.72   104.3 1977.35   140.2 1965.33   169.5  1952.4
   185.8 1941.29   198.8  1934.4   215.1 1931.83     251 1930.15   267.3  1926.5
   322.7 1931.66   400.9 1931.42   443.3 1928.86     489  1929.8   515.1 1926.82
     525 1927.14   531.5 1929.44   538.1 1930.79  587.371929.692  604.531929.589
  644.181930.587   659.2 1930.97  674.171935.882   682.2 1938.53   711.7 1941.08
   773.9 1943.59   790.3 1948.42   816.6 1950.66   882.1 1961.93  1098.4 1977.73
#Mann= 7 ,-1 , 0
       0     .12       0     489     .04       0   531.5     .12       0
  587.37    .016       0  604.53     .12       0  644.18    .016       0
  674.17     .12       0
#XS Ineff= 2 , 0
          328.73 1932.15
Permanent Ineff=
       F       F
Bank Sta=489,531.5
XS Rating Curve= 0 ,0
Exp/Cntr=0.5,0.3

Type RM Length L Ch R = 1 ,19085   ,173.2,173.2,173.2
XS GIS Cut Line= 3
     2152328.801      266746.255     2152919.947      266962.401
      2153378.28      266868.651
#Sta/Elev= 30
       0 2044.79    91.8  2007.4   121.3 1996.96   131.1 1995.96   183.6 1978.79
   190.1 1974.08   226.2 1936.59     236    1929   242.6 1925.81   252.4 1925.12
   298.3  1928.3   337.7 1926.37   380.3 1927.75   390.1 1924.87   419.6 1927.71
   475.3 1926.19   488.5 1927.61   501.6 1926.45   524.5 1928.79   537.6 1927.52
   603.2 1928.56     613 1930.03   626.1 1935.42  649.841936.996  679.991938.989
   701.4 1940.73   724.3 1952.41   734.1 1954.78     865 1962.54  1097.2 1981.41
#Mann= 5 ,-1 , 0
       0     .12       0   380.3     .04       0   419.6     .12       0
  649.84    .016       0  679.99     .12       0
#XS Ineff= 2 , 0
                          583.96         1930.35
Permanent Ineff=
       F       F
Bank Sta=380.3,419.6
XS Rating Curve= 0 ,0
Exp/Cntr=0.3,0.1

Type RM Length L Ch R = 1 ,18912   ,262.7,262.7,262.7
XS GIS Cut Line= 2
     2152223.793      267038.184      2153211.64       267031.24
#Sta/Elev= 30
       0 2108.44     9.8 2101.26    26.2 2099.73    32.7 2097.49    62.2 2078.02
    88.3 2069.54   114.5 2055.92   153.7 2039.66   176.6 2031.72   209.4 2023.41
     229 2005.33   251.9 1978.02   304.2  1929.1   310.8 1925.05   336.9 1922.34
     386 1925.18   405.6 1923.38   485.9 1925.31   500.9 1925.33   516.8  1926.8
   588.8 1924.48   605.2 1926.51   683.7 1926.47   703.3 1927.58   719.6 1934.45
  745.711934.598  775.251947.522   824.3 1953.36   948.6 1961.94   987.9 1962.62
#Mann= 5 ,-1 , 0
       0     .12       0   485.9     .04       0   500.9     .12       0
  745.71    .016       0  775.25     .12       0
Bank Sta=485.9,500.9
XS Rating Curve= 0 ,0
Exp/Cntr=0.3,0.1

Type RM Length L Ch R = 1 ,18649   ,294.4,294.4,294.4
XS GIS Cut Line= 4
     2152208.126      267240.126     2152596.096      267259.387
     2152709.349      267293.164     2153117.466      267287.072
#Sta/Elev= 30
       0 2130.54    26.1 2117.74    65.3 2103.85    84.9 2094.85   101.2 2085.22
   133.8 2077.49   146.9 2069.02     222  2031.8     235 2022.88   280.7 1979.33
   342.8 1924.88   349.3  1921.8   375.4 1918.91   391.6 1919.04   410.8 1921.77
   442.8 1921.01   452.3 1919.11   471.5 1921.33   519.7 1922.66   542.6 1921.02
   598.1 1924.31   718.9 1923.87   751.5  1925.8  766.771925.323   777.6 1925.29
   787.4  1931.6  796.311934.649   833.2 1937.87   895.2  1940.2   914.8 1938.24
#Mann= 5 ,-1 , 0
       0     .12       0   442.8     .04       0   471.5     .12       0
  766.77    .016       0  796.31     .12       0
Bank Sta=442.8,471.5
XS Rating Curve= 0 ,0
Exp/Cntr=0.3,0.1

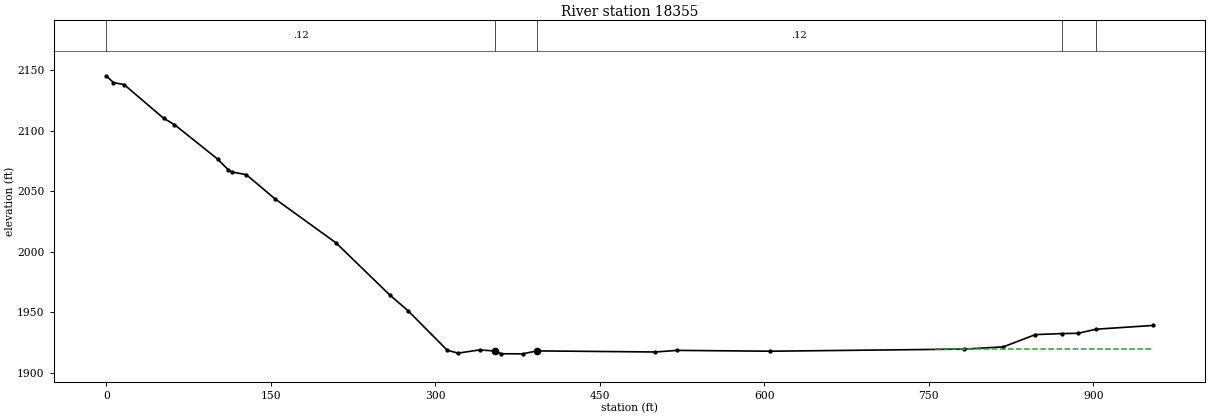
Type RM Length L Ch R = 1 ,18355   ,319.3,319.3,319.3
XS GIS Cut Line= 3
      2152196.73      267503.775     2152943.803      267565.369
     2153136.532      267495.828
#Sta/Elev= 30
       0 2145.34     6.6 2139.73    16.4 2138.04    52.4 2110.19    62.2 2105.02
   101.5 2076.58   111.3 2067.67   114.6 2065.85   127.7 2063.67   153.8 2043.74
   209.5 2007.32   258.6 1964.19     275 1951.41     311 1918.56   320.8  1916.2
   340.4 1918.84  354.92 1917.92   360.1 1915.67   379.7 1915.61   392.8 1918.05
   500.8 1917.14   520.5 1918.47   605.6 1917.78   782.1 1919.53   817.9 1921.36
   847.2  1931.5  871.071932.356   886.2 1932.58  902.481935.948   954.5 1939.07
#Mann= 5 ,-1 , 0
       0     .12       0  354.92     .04       0   392.8     .12       0
  871.07    .016       0  902.48     .12       0
#XS Ineff= 2 , 0
                          755.58         1919.91
Permanent Ineff=
       F       F
Bank Sta=354.92,392.8
XS Rating Curve= 0 ,0
Exp/Cntr=0.3,0.1