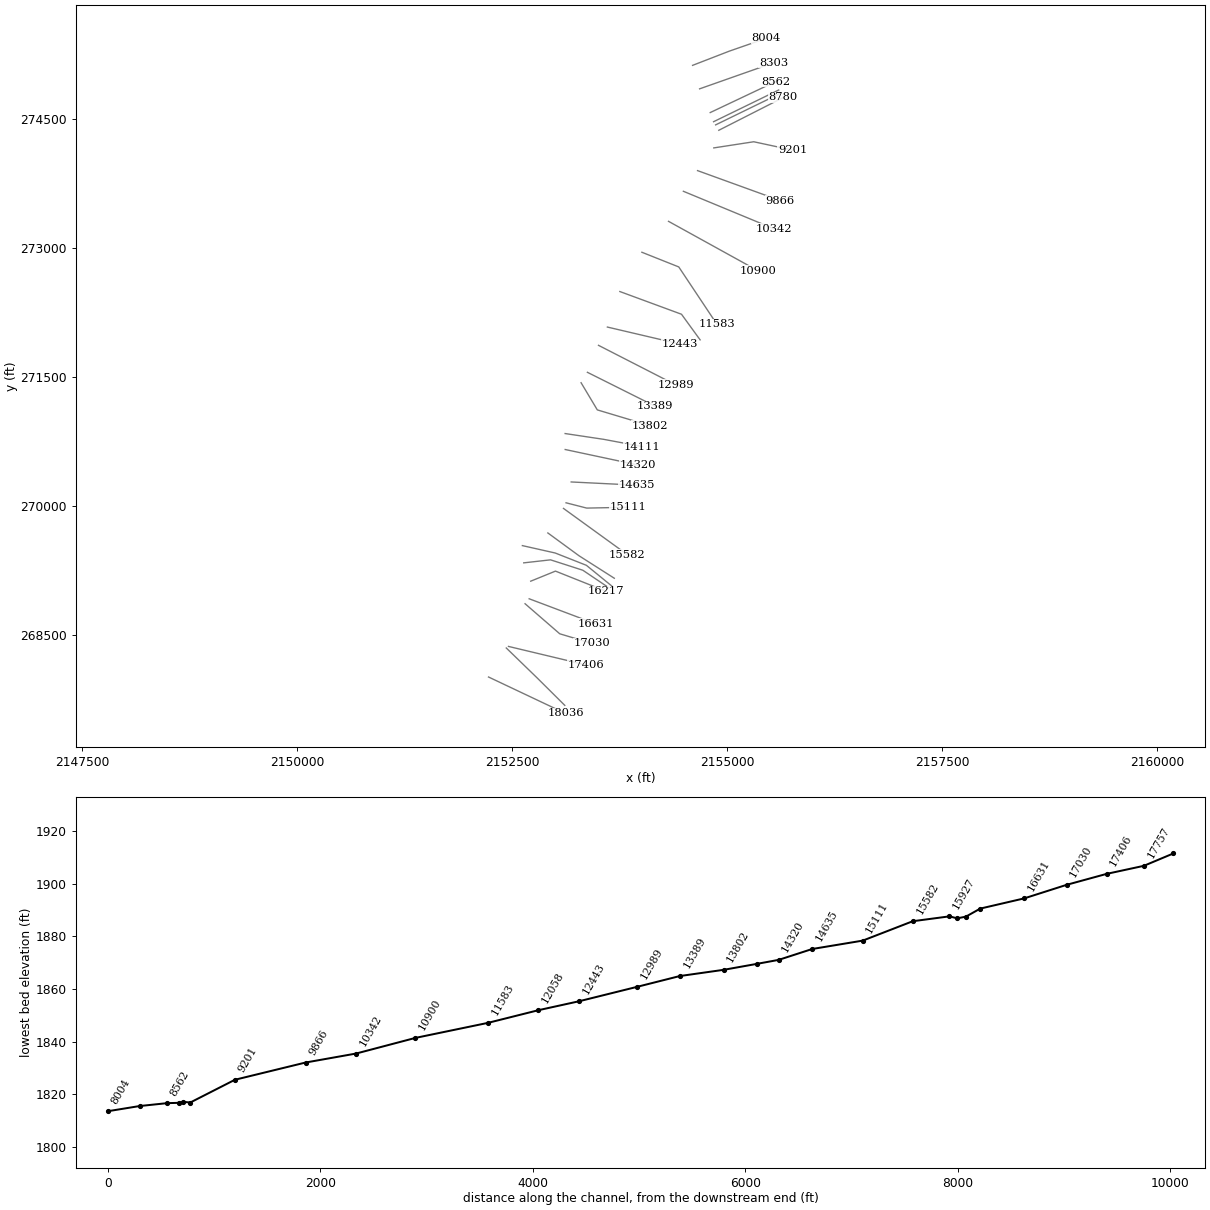
HEC-RAS study HARTSRN.prj: HARTSRN

--- HARTSRN.g01 (geometry) --- (continued)

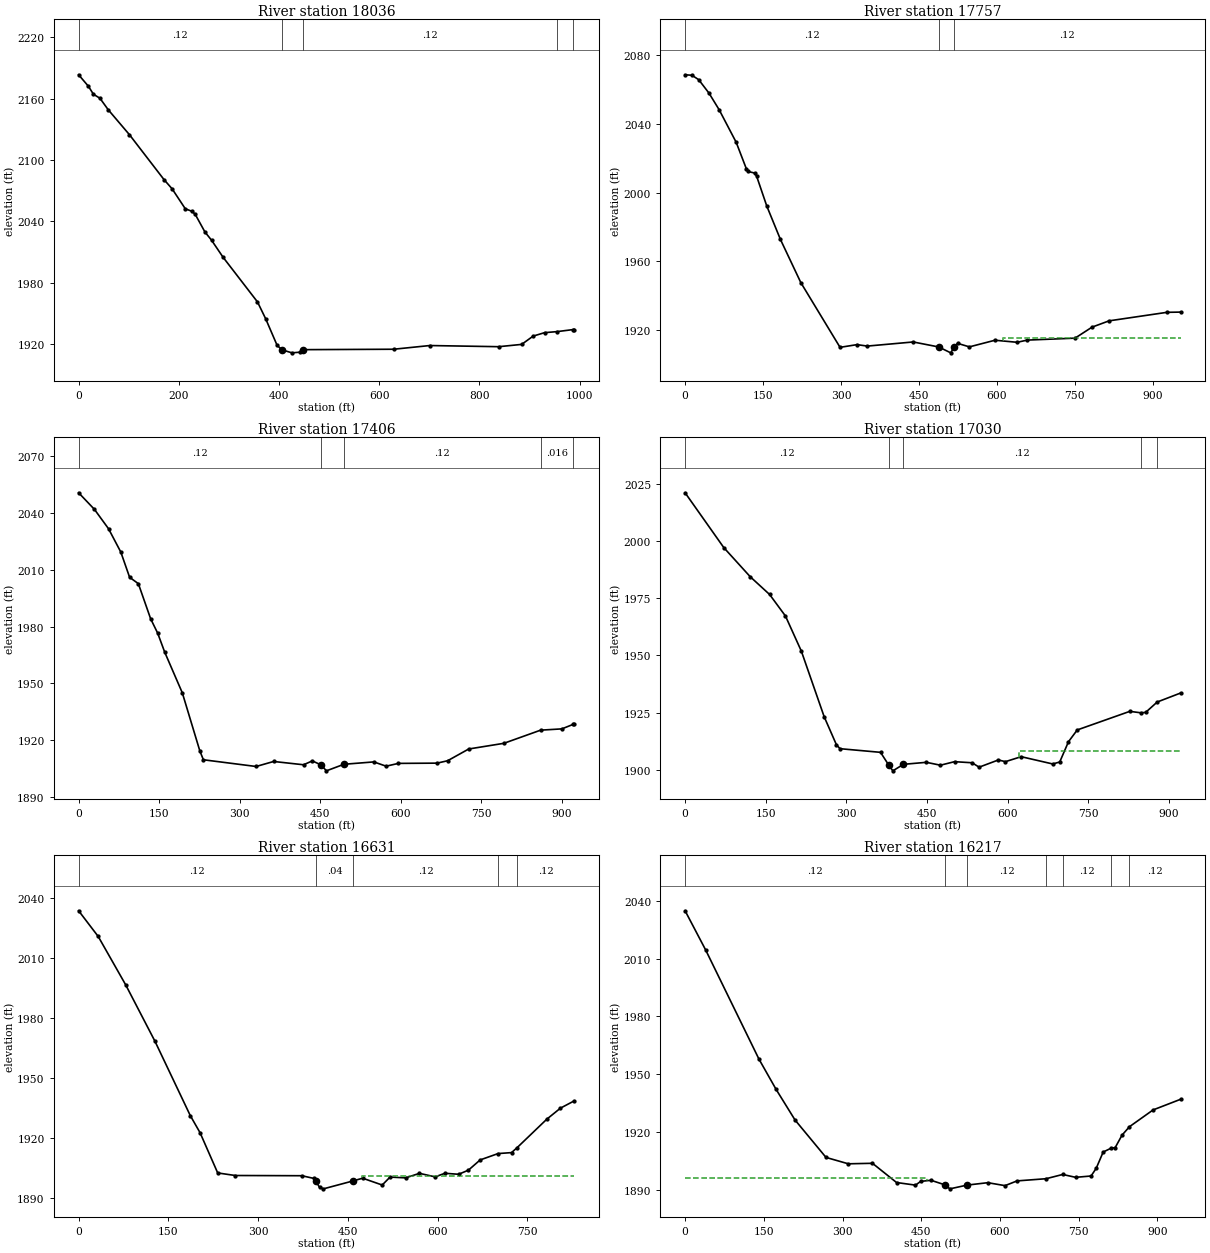
Type RM Length L Ch R = 1 ,18036   ,278.7,278.7,278.7
XS GIS Cut Line= 2
     2152224.547       268006.46     2153118.649      267583.251
#Sta/Elev= 30
       0 2183.45    19.6 2172.16    29.5 2164.43    42.6 2160.46      59  2149.3
   101.5 2124.81   170.3 2081.01   186.7 2071.86   212.9 2052.42     226 2049.96
   232.6 2047.09   252.2 2029.64   265.3 2021.69   288.2 2005.08     357 1961.32
   373.4  1944.8   396.3 1918.73   406.2 1914.41   425.8 1911.51   442.2 1912.16
   448.8 1914.62   628.9 1915.03     701 1918.65   838.5 1917.52   884.4 1919.77
   907.3 1927.88   930.2 1931.25  954.841932.255  987.521934.275   989.2  1934.3
#Mann= 5 ,-1 , 0
       0     .12       0   406.2     .04       0   448.8     .12       0
  954.84    .016       0  987.52     .12       0
Bank Sta=406.2,448.8
XS Rating Curve= 0 ,0
Exp/Cntr=0.3,0.1

Type RM Length L Ch R = 1 ,17757   ,350.4,350.4,350.4
XS GIS Cut Line= 3
     2152431.133      268344.053     2152790.868       267995.14
     2153111.762      267676.507
#Sta/Elev= 30
       0 2068.45    13.1 2068.18    26.2 2065.59    45.9 2057.81    65.5 2048.13
    98.3 2029.19   117.9 2013.76   121.2 2012.22   134.3 2011.28   137.6  2009.5
   157.2  1992.1   183.4 1972.73   222.7 1947.59   298.1 1909.99   330.8 1911.56
   350.5 1910.72   438.9 1913.11     488 1910.21     511 1906.79   517.5 1910.07
   524.1 1912.32     547 1910.26   596.2 1914.12   638.8 1912.92   658.4  1914.2
   750.2 1915.33     783 1921.74   815.7 1925.39   927.2 1930.35   953.4 1930.48
#Mann= 3 ,-1 , 0
       0     .12       0     488     .04       0   517.5     .12       0
#XS Ineff= 2 , 0
                          612.47         1915.34
Permanent Ineff=
       F       F
Bank Sta=488,517.5
XS Rating Curve= 0 ,0
Exp/Cntr=0.3,0.1

Type RM Length L Ch R = 1 ,17406   ,376.4,376.4,376.4
XS GIS Cut Line= 2
     2152457.013      268362.114      2153355.09      268147.529
#Sta/Elev= 30
       0 2050.72    29.5 2041.93    55.7 2031.72    78.6 2019.38      95 2006.04
   111.3 2002.67   134.2  1984.1   147.3 1976.51   160.4 1966.47   193.2 1944.96
   225.9 1914.23   232.5 1909.58   330.7 1906.03   363.4 1908.68   419.1 1906.94
   435.5 1908.98   451.9 1906.84   461.7 1903.73   494.4  1907.2   550.1 1908.45
     573 1906.19   595.9 1907.67     668  1907.8   687.6 1909.07   726.9 1915.28
   792.4 1918.28  860.871925.233   900.4 1925.91  921.611928.308   923.4 1928.46
#Mann= 5 ,-1 , 0
       0     .12       0   451.9     .04       0   494.4     .12       0
  860.87    .016       0  921.61     .12       0
Bank Sta=451.9,494.4
XS Rating Curve= 0 ,0
Exp/Cntr=0.3,0.1

Type RM Length L Ch R = 1 ,17030   ,399.5,399.5,399.5
XS GIS Cut Line= 3
     2152649.742      268858.838     2153053.082      268509.144
     2153424.631      268397.878
#Sta/Elev= 30
       0    2021      72 1997.05   121.2 1984.32   157.2 1976.58   186.7 1967.17
   216.2 1951.86   258.7 1923.18   281.6 1910.89   288.2 1909.24   363.5 1907.65
   378.7 1902.11   386.4 1899.57   406.1 1902.41   448.7 1903.29   474.9 1902.03
   501.1 1903.57   533.8  1903.1   546.9 1901.17   582.7 1904.32   595.8 1903.58
   625.1 1905.75   683.8 1902.57   696.8 1903.43   713.1 1912.29   729.4 1917.43
   827.2 1925.55  847.281924.925   856.5 1925.07  878.111929.626   921.7 1933.56
#Mann= 5 ,-1 , 0
       0     .12       0   378.7     .04       0   406.1     .12       0
  847.28    .016       0  878.11     .12       0
#XS Ineff= 2 , 0
                          620.27         1908.04
Permanent Ineff=
       F       F
Bank Sta=378.7,406.1
XS Rating Curve= 0 ,0
Exp/Cntr=0.3,0.1

Type RM Length L Ch R = 1 ,16631   ,413.7,413.7,413.7
XS GIS Cut Line= 2
     2152697.428      268916.458     2153472.317      268624.384
#Sta/Elev= 30
       0 2033.48    32.7 2020.64    78.6 1996.46   127.6  1968.2   186.6 1931.04
   202.9  1922.5   232.4 1902.37   261.8 1901.09   373.1 1900.98   392.8 1899.65
  396.571898.242   402.6 1895.14   409.1 1894.42   458.2 1898.35   474.6 1899.74
   507.3 1896.33   520.4  1900.3   546.6 1899.91   569.5 1902.17   595.7 1900.41
   612.1  1902.2     635  1901.7   651.4 1903.77     671 1908.88  700.971912.062
   723.4 1912.54  732.54 1914.96   782.3 1929.24   805.2 1934.78   828.1  1938.4
#Mann= 5 ,-1 , 0
       0     .12       0  396.57     .04       0   458.2     .12       0
  700.97    .016       0  732.54     .12       0
#XS Ineff= 2 , 0
                          473.27         1900.84
Permanent Ineff=
       F       F
Bank Sta=396.57,458.2
XS Rating Curve= 0 ,0
Exp/Cntr=0.3,0.1

Type RM Length L Ch R = 1 ,16217   ,135.7,135.7,135.7
XS GIS Cut Line= 3
      2152715.31      269121.108      2153003.41      269238.334
      2153591.53      269003.881
#Sta/Elev= 30
       0 2034.83    39.3 2014.43   140.8 1957.82   173.5  1942.1   209.5 1926.25
   268.5 1906.84     311 1903.53     357  1903.8   402.9 1893.82     439 1892.46
   448.8  1894.4   468.5 1894.98   494.7 1892.65   504.6 1890.54   537.4 1892.49
   576.8 1893.73   609.6  1892.2   632.5 1894.66  687.731895.793  719.521898.001
   744.1 1896.51   773.6 1897.21   783.4 1901.24   796.6 1909.64  811.081911.562
   819.5 1911.95   832.6 1918.43  846.721922.786   891.7 1931.49   944.2 1937.02
#Mann= 7 ,-1 , 0
       0     .12       0   494.7     .04       0   537.4     .12       0
  687.73    .016       0  719.52     .12       0  811.08    .016       0
  846.72     .12       0
#XS Ineff= 2 , 0
          461.02 1895.95
Permanent Ineff=
       F       F
Bank Sta=494.7,537.4
XS Rating Curve= 0 ,0
Exp/Cntr=0.5,0.3

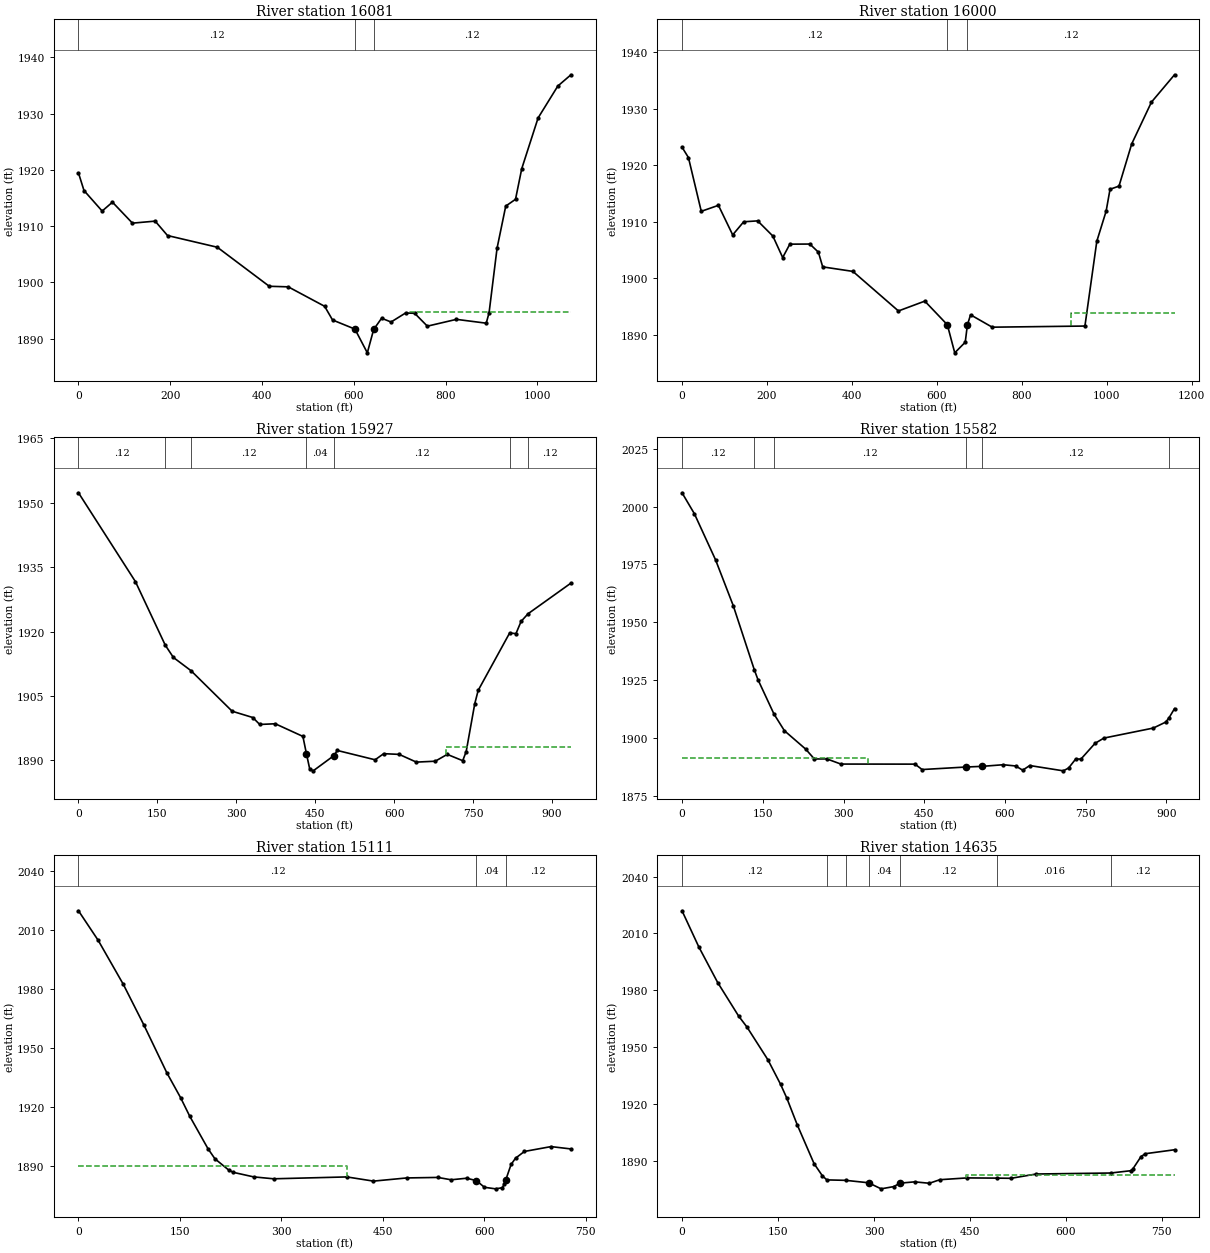
Type RM Length L Ch R = 1 ,16081   ,81.6,81.6,81.6
XS GIS Cut Line= 4
2152634.30907363269334.4099916592152946.25126915269369.423911564
2153321.85513722269248.4667337112153624.24808185269044.749381538
#Sta/Elev= 30
       0 1919.44      12 1916.32    51.6 1912.67      74 1914.25   117.6 1910.52
   167.1 1910.88     194 1908.32   302.5 1906.24   415.7  1899.3   457.1  1899.2
   536.4 1895.74   553.6 1893.31   602.4 1891.69   629.4 1887.47   643.2 1891.62
   660.5 1893.62   681.1 1892.95   712.7 1894.55   732.5  1894.5   760.2 1892.21
   823.5 1893.42   888.5 1892.74   894.7  1894.6   912.1 1906.07     931 1913.55
   952.3 1914.76   965.9 1920.21  1001.5 1929.22  1044.5 1934.89  1073.1 1936.89
#Mann= 3 , 0 , 0
       0     .12       0   602.4     .04       0   643.2     .12       0
#XS Ineff= 2 , 0
                          722.94         1894.76
Permanent Ineff=
       F       F
Bank Sta=602.4,643.2
XS Rating Curve= 0 ,0
Exp/Cntr(USF)=0,0
Exp/Cntr=0.5,0.3

Type RM Length L Ch R = 1 ,16000   ,72.7,72.7,72.7
XS GIS Cut Line= 4
2152618.39365549269534.9442602042153000.36369082269449.001002256
2153363.23522438 269305.762239012153656.07891813269067.030966932
#Sta/Elev= 30
       0 1923.23    15.1 1921.39    45.3 1911.88    85.7 1912.94   119.3 1907.71
   145.2 1910.03   178.1 1910.19   213.8 1907.51     237  1903.7   253.8 1906.07
   300.9 1906.09   321.1 1904.65   331.2 1902.05   402.3 1901.25   509.5 1894.25
   571.6 1895.99  624.671891.808   642.1 1886.84   666.8 1888.72  671.84 1891.76
   679.3 1893.57   730.3 1891.38   948.6 1891.58   976.6 1906.59   998.5  1911.9
  1007.7 1915.78  1028.8 1916.34  1058.7  1923.8  1105.2  1931.2  1159.5 1936.04
#Mann= 3 , 0 , 0
       0     .12       0  624.67     .04       0  671.84     .12       0
#XS Ineff= 2 , 0
                          915.37         1893.89
Permanent Ineff=
       F       F
Bank Sta=624.67,671.84
XS Rating Curve= 0 ,0
Exp/Cntr(USF)=0,0
Exp/Cntr=0.5,0.3

Type RM Length L Ch R = 1 ,15927   ,345.3,345.3,345.3
XS GIS Cut Line= 3
     2152914.905      269682.215     2153277.549       269416.75
     2153687.884      269155.368
#Sta/Elev= 30
       0 1952.27   108.3 1931.59  164.921916.828   180.4 1913.96  213.841910.888
     292 1901.46   331.3 1899.99   344.4 1898.38     374 1898.54   426.5  1895.6
   433.31891.514   439.6 1887.94   446.1 1887.59   485.3 1891.12   491.9 1892.33
   563.7 1890.16     580 1891.58   609.4 1891.42   642.1 1889.62     678 1889.83
   700.8 1891.42   730.2 1889.95   736.8 1892.07   753.1 1903.21   759.6 1906.31
  819.411919.659   831.4 1919.51   841.2 1922.36  854.431924.134   935.9 1931.26
#Mann= 7 ,-1 , 0
       0     .12       0  164.92    .016       0  213.84     .12       0
   433.3     .04       0   485.3     .12       0  819.41    .016       0
  854.43     .12       0
#XS Ineff= 2 , 0
                          698.22         1893.12
Permanent Ineff=
       F       F
Bank Sta=433.3,485.3
XS Rating Curve= 0 ,0
Exp/Cntr=0.3,0.1

Type RM Length L Ch R = 1 ,15582   ,471,471,471
XS GIS Cut Line= 2
     2153096.794      269967.525     2153837.905      269431.063
#Sta/Elev= 30
       0 2005.96      23 1996.88    62.3 1976.96    95.1  1957.2   134.31929.424
     141  1925.2  170.761910.319   190.2 1903.09   229.5 1895.18   245.9 1890.86
   268.9 1890.91   295.1 1888.67   432.8 1888.64     446  1886.3   526.7 1887.38
   557.5 1887.68   596.8 1888.38   619.8 1887.84   632.9 1886.03     646 1888.03
   708.3 1885.74   718.2 1886.97   731.3 1890.84   741.1 1890.83   767.3 1897.63
   783.7  1899.9   875.6 1904.24   898.5 1906.81  904.49 1908.57   914.9 1912.64
#Mann= 6 ,-1 , 0
       0     .12       0   134.3    .016       0  170.76     .12       0
   526.7     .04       0   557.5     .12       0  904.49    .016       0
#XS Ineff= 2 , 0
          346.33 1891.48
Permanent Ineff=
       F       F
Bank Sta=526.7,557.5
XS Rating Curve= 0 ,0
Exp/Cntr=0.3,0.1

Type RM Length L Ch R = 1 ,15111   ,475.3,475.3,475.3
XS GIS Cut Line= 3
     2153126.597      270033.092     2153367.011      269971.499
2153846.94776207269981.161851638
#Sta/Elev= 30
       02019.551  29.1572004.537  66.3071982.193  96.5591961.668 130.6561937.283
 150.9771924.677 164.524 1915.23 191.6181898.681 201.7791893.622 222.0991887.927
 228.6671886.762 259.0071884.438  288.541883.469  396.831884.418 436.2081882.291
  485.431883.906 531.3711884.162  551.061882.968 574.0311883.762   588.5 1882.52
 600.283 1879.16  616.69 1878.37 626.5351878.925 629.816 1880.75  631.621882.689
 639.6611890.736 646.2241893.913  659.351897.348 698.7281899.814 728.2131898.629
#Mann= 3 ,-1 , 0
       0     .12       0   588.5     .04       0  631.62     .12       0
#XS Ineff= 2 , 0
          397.54 1889.91
Permanent Ineff=
       F       F
Bank Sta=588.5,631.62
XS Rating Curve= 0 ,0
Exp/Cntr=0.3,0.1

Type RM Length L Ch R = 1 ,14635   ,315.5,315.5,315.5
XS GIS Cut Line= 2
     2153186.204      270275.494     2153955.132      270237.743
#Sta/Elev= 30
       0 2021.93    26.2 2002.89    55.7 1984.08    88.4 1966.41   101.6 1960.53
   134.3 1943.26     154 1930.38   163.8 1923.06   180.2 1908.89   206.4 1888.49
   219.5 1882.02  226.381879.912  255.951879.671   291.6 1878.39   311.2 1875.19
   330.9 1876.37   340.7 1878.19   363.6 1878.88   386.6 1878.13     403 1880.01
   445.5 1880.96  492.531880.847   514.3 1880.75   553.6 1883.01  669.97 1883.54
   701.1 1884.74   704.3  1885.5   717.4 1892.19     724 1893.72   769.8 1895.81
#Mann= 7 ,-1 , 0
       0     .12       0  226.38    .016       0  255.95     .12       0
   291.6     .04       0   340.7     .12       0  492.53    .016       0
  669.97     .12       0
#XS Ineff= 2 , 0
                          443.65         1882.28
Permanent Ineff=
       F       F
Bank Sta=291.6,340.7
XS Rating Curve= 0 ,0
Exp/Cntr=0.3,0.1

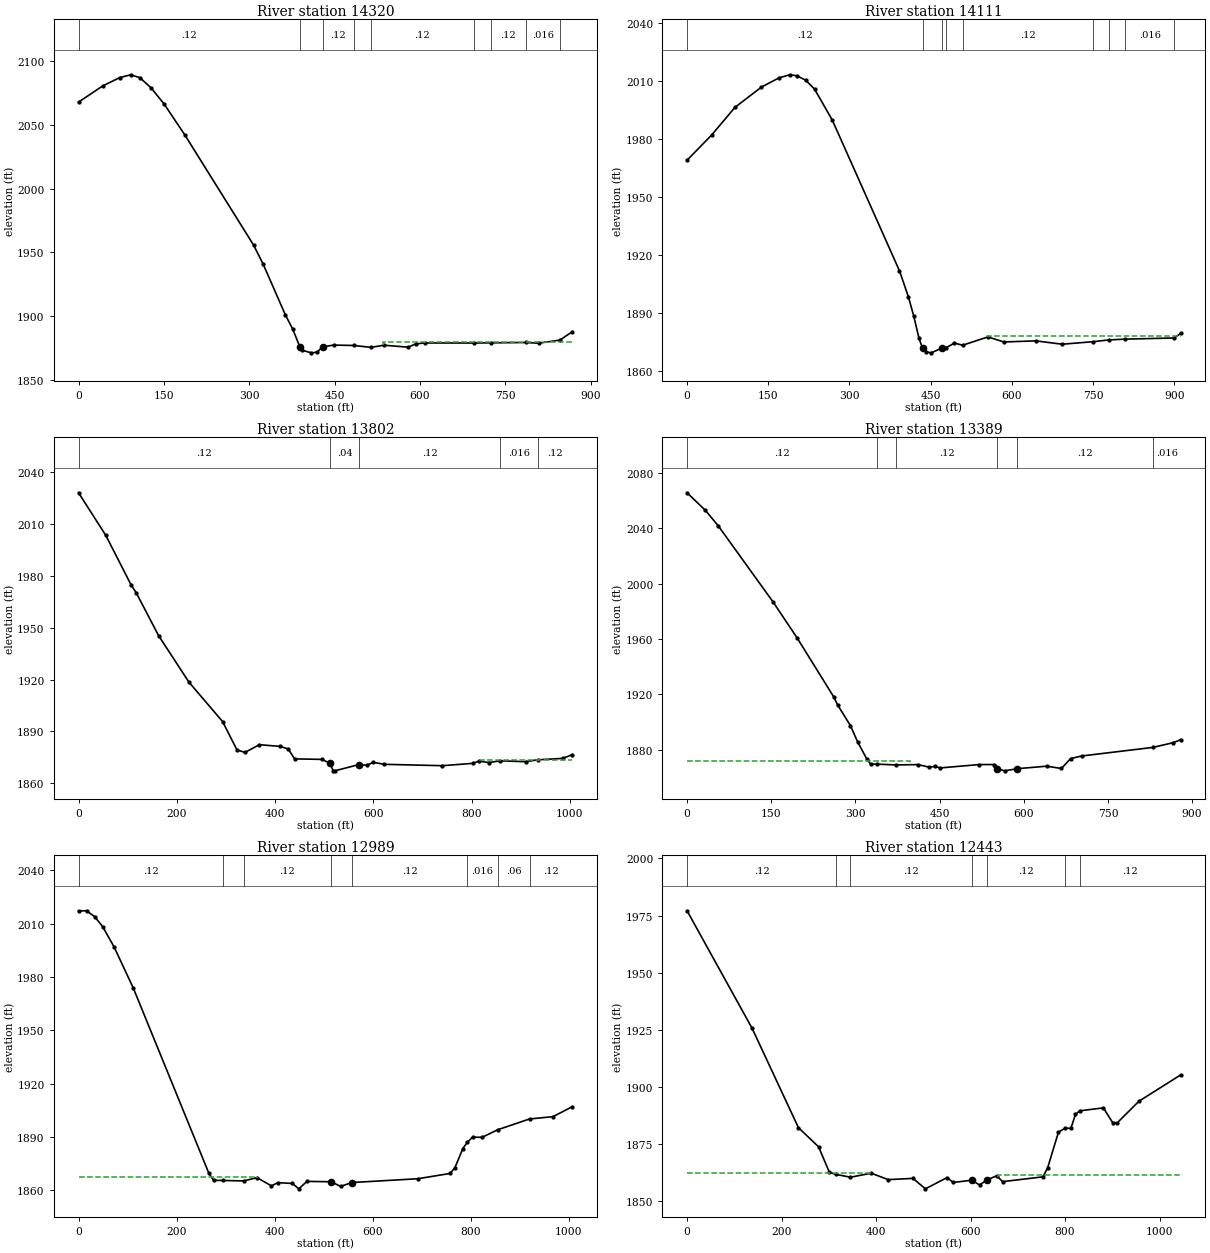
Type RM Length L Ch R = 1 ,14320   ,209,209,209
XS GIS Cut Line= 2
     2153116.663      270653.004     2153965.067      270472.196
#Sta/Elev= 30
       0 2068.06    42.6 2080.81      72 2087.24    91.7 2089.54     108  2087.2
   127.7 2079.15   150.6 2066.46   186.6  2042.4   307.7 1955.65   324.1 1941.08
   363.4 1900.94   376.4  1889.7  388.891875.767   392.8 1873.08   409.2 1871.06
     419 1871.54   428.8 1875.74   448.5 1877.15  483.471876.857  513.671875.369
   536.8 1877.05   579.4  1875.5   592.5  1878.1   608.9 1878.82  694.881878.792
  725.081878.921  785.481879.185   808.5 1878.64  845.881881.071   867.5  1887.6
#Mann= 9 ,-1 , 0
       0     .12       0  388.89     .04       0   428.8     .12       0
  483.47    .016       0  513.67     .12       0  694.88    .016       0
  725.08     .12       0  785.48    .016       0  845.88     .12       0
#XS Ineff= 2 , 0
                          534.52         1879.34
Permanent Ineff=
       F       F
Bank Sta=388.89,428.8
XS Rating Curve= 0 ,0
Exp/Cntr=0.3,0.1

Type RM Length L Ch R = 1 ,14111   ,308.5,308.5,308.5
XS GIS Cut Line= 3
     2153115.843      270838.719     2153565.377      270771.252
     2154014.916      270686.794
#Sta/Elev= 30
       0  1969.1    45.8 1982.22    88.3 1996.36   137.4 2006.89     170 2011.67
   189.7 2013.25   202.8 2012.77   219.1 2010.44   235.5 2005.86   268.2 1989.87
   392.4 1911.92   408.8 1898.56   418.6 1888.66   428.4 1877.14     435 1871.82
   441.5 1869.99   451.3 1869.51   470.9 1872.01  479.111872.222   493.8 1874.56
  509.171873.454   555.8 1877.74   585.3 1875.13   644.1  1875.7   693.1 1873.97
   749.61875.254  779.65  1876.2  809.711876.593  899.871877.195     912 1879.51
#Mann= 9 ,-1 , 0
       0     .12       0     435     .04       0   470.9     .12       0
  479.11    .016       0  509.17     .12       0   749.6    .016       0
  779.65     .12       0  809.71    .016       0  899.87     .12       0
#XS Ineff= 2 , 0
                          554.57         1878.01
Permanent Ineff=
       F       F
Bank Sta=435,470.9
XS Rating Curve= 0 ,0
Exp/Cntr=0.3,0.1

Type RM Length L Ch R = 1 ,13802   ,413.6,413.6,413.6
XS GIS Cut Line= 3
     2153301.444       271429.88     2153490.199      271113.963
     2154100.176      270931.169
#Sta/Elev= 30
       0 2027.81    55.4 2003.27   107.5 1974.34   117.2 1970.21   162.8 1945.41
   224.7 1918.48   293.1 1895.76   322.4 1879.41   338.7 1877.89     368 1882.37
   410.5 1881.39   426.8  1879.9   439.8 1874.19   495.4 1873.89  511.881871.633
   518.2 1867.39   521.5 1867.28   570.5 1870.88   586.8 1870.52   599.9 1872.19
   622.7 1871.04   740.3 1870.25   802.3  1871.6   815.4 1872.92     835 1872.04
  858.751873.068   910.1 1872.54  934.181873.646   985.2 1874.46  1004.8 1876.59
#Mann= 5 ,-1 , 0
       0     .12       0  511.88     .04       0   570.5     .12       0
  858.75    .016       0  934.18     .12       0
#XS Ineff= 2 , 0
                          817.82          1873.6
Permanent Ineff=
       F       F
Bank Sta=511.88,570.5
XS Rating Curve= 0 ,0
Exp/Cntr=0.3,0.1

Type RM Length L Ch R = 1 ,13389   ,399.9,399.9,399.9
XS GIS Cut Line= 2
     2153374.959       271551.08     2154161.769      271157.675
#Sta/Elev= 30
       0  2065.5    32.7 2052.81    55.6 2041.64   153.7 1986.49   196.2 1960.74
   261.6 1918.08   268.2 1912.51     291 1897.61   304.1 1885.65   320.5  1873.3
     327  1869.7  338.891869.732  371.911869.172     412  1869.4   431.7 1867.51
   441.5  1868.1   451.3 1867.02     520 1869.42   546.1 1869.46   549.4 1868.74
   552.7 1866.46   565.7 1864.91   588.6 1866.47     641 1868.28   667.1  1866.6
   683.5 1873.77   703.1 1875.62  830.071881.812   866.6 1885.26   879.7 1887.39
#Mann= 6 ,-1 , 0
       0     .12       0  338.89    .016       0  371.91     .12       0
   552.7     .04       0   588.6     .12       0  830.07    .016       0
#XS Ineff= 2 , 0
          397.55  1871.7
Permanent Ineff=
       F       F
Bank Sta=552.7,588.6
XS Rating Curve= 0 ,0
Exp/Cntr=0.3,0.1

Type RM Length L Ch R = 1 ,12989   ,546.2,546.2,546.2
XS GIS Cut Line= 2
     2153504.107       271865.01     2154400.197      271406.037
#Sta/Elev= 30
       0 2017.15    16.4 2017.22    32.8 2013.95    49.2 2008.31    72.2 1997.05
   111.5 1973.88   265.6 1869.71   275.5  1865.6  294.981865.539  336.731865.277
     364 1867.12   393.5 1862.49   406.6 1864.34   436.2 1863.84   449.3 1860.83
   465.7 1865.02   514.9 1864.82   534.6 1862.21   557.5 1864.38     692 1866.51
   757.6 1869.48   767.4  1872.6   783.8  1883.5  792.791886.967   803.5 1889.88
   823.1 1889.83  854.991894.063  919.781900.136   967.4 1901.41  1006.8 1907.01
#Mann= 8 ,-1 , 0
       0     .12       0  294.98    .016       0  336.73     .12       0
   514.9     .04       0   557.5     .12       0  792.79    .016       0
  854.99     .06       0  919.78     .12       0
#XS Ineff= 2 , 0
          364.81 1867.72
Permanent Ineff=
       F       F
Bank Sta=514.9,557.5
XS Rating Curve= 0 ,0
Exp/Cntr=0.3,0.1

Type RM Length L Ch R = 1 ,12443   ,384.2,384.2,384.2
XS GIS Cut Line= 2
     2153607.426      272077.6072154452.25491236271879.600509139
#Sta/Elev= 30
       0 1977.08   137.6 1925.65   235.8 1882.11   278.4 1873.75   301.3 1862.53
  315.211861.691  345.551860.435   389.8 1862.19   425.8 1859.38   478.2 1859.93
   504.4 1855.35   550.3 1860.28   563.4 1858.14   602.7 1859.13     619 1857.05
   635.4 1859.29   655.1 1861.06   668.2  1858.5   753.4 1860.61   763.2 1864.56
   786.1 1880.17  800.621881.954   812.3 1881.79   822.1  1887.9  830.951889.505
   881.1 1890.79   900.7 1884.38   910.6 1884.26   956.4  1893.7  1044.9 1905.24
#Mann= 7 ,-1 , 0
       0     .12       0  315.21    .016       0  345.55     .12       0
   602.7     .04       0   635.4     .12       0  800.62    .016       0
  830.95     .12       0
#XS Ineff= 2 , 0
          391.54 1862.28  657.46         1861.61
Permanent Ineff=
       F       F
Bank Sta=602.7,635.4
XS Rating Curve= 0 ,0
Exp/Cntr=0.3,0.1

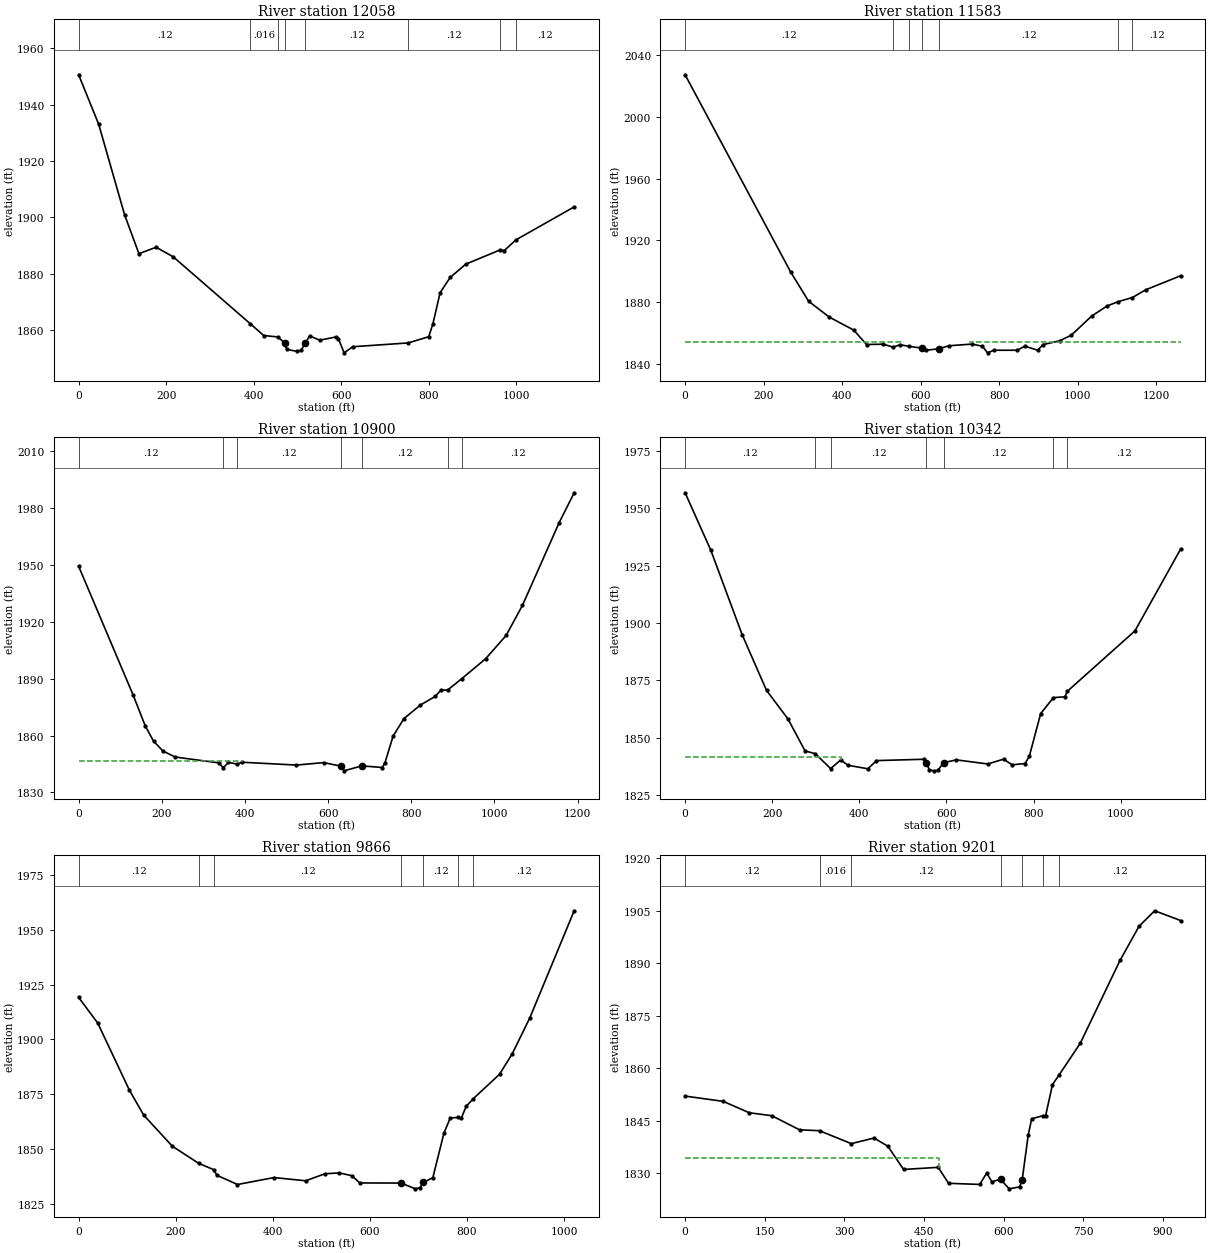
Type RM Length L Ch R = 1 ,12058   ,475.5,475.5,475.5
XS GIS Cut Line= 3
     2153752.469      272490.881     2154469.738      272226.624
      2154686.31       271928.59
#Sta/Elev= 30
       0 1950.54    45.9 1932.98     105 1900.92   137.8  1887.1   177.2 1889.38
   216.5 1885.96  392.811862.203   423.2 1858.07  455.761857.574  470.651855.451
   475.7 1853.13   498.7  1852.5   508.5 1852.78   518.4  1855.5   528.2 1857.94
   551.2 1856.42   587.2 1857.55   593.8 1856.95   606.9 1851.94   626.6  1854.1
  753.131855.451   800.3 1857.65     810 1862.28   826.3 1873.26   849.2 1878.66
     885 1883.39  962.961888.403   973.1 1888.22  999.471891.985  1132.8 1903.69
#Mann= 8 ,-1 , 0
       0     .12       0  392.81    .016       0  455.76     .12       0
  470.65     .04       0   518.4     .12       0  753.13     .12       0
  962.96    .016       0  999.47     .12       0
Bank Sta=470.65,518.4
XS Rating Curve= 0 ,0
Exp/Cntr=0.3,0.1

Type RM Length L Ch R = 1 ,11583   ,683.3,683.3,683.3
XS GIS Cut Line= 3
     2154008.778      272947.867     2154437.948      272776.994
     2154881.025      272111.384
#Sta/Elev= 30
       0 2027.21   268.6 1899.54   314.5  1880.5   366.9 1870.29   429.2 1861.86
   461.9 1852.51   504.5 1852.72  529.651850.809   547.1 1852.37  570.931851.308
   602.8 1850.18   612.7 1848.72   645.4 1849.79   671.7  1851.7   730.6  1852.8
   756.9 1851.37     770 1847.12   786.4 1848.81   845.4  1848.8     865 1851.46
   897.8 1848.78   910.9 1852.43   953.5 1854.91     983 1858.52  1035.4 1871.03
  1074.7 1877.55 1103.141880.304 1138.621882.955    1173 1887.98  1261.5 1897.05
#Mann= 7 ,-1 , 0
       0     .12       0  529.65    .016       0  570.93     .12       0
   602.8     .04       0   645.4     .12       0 1103.14    .016       0
 1138.62     .12       0
#XS Ineff= 2 , 0
          548.78 1854.26  724.94         1853.86
Permanent Ineff=
       F       F
Bank Sta=602.8,645.4
XS Rating Curve= 0 ,0
Exp/Cntr=0.3,0.1

Type RM Length L Ch R = 1 ,10900   ,557.3,557.3,557.3
XS GIS Cut Line= 2
     2154318.734      273307.495     2155361.854      272731.296
#Sta/Elev= 30
       0 1949.32     131 1881.43   160.4 1865.02   180.1 1857.08     203 1851.82
   232.4 1848.68   337.2 1845.61  347.751842.985   360.1 1845.84  381.491844.961
   392.9 1845.94   523.8 1844.44   589.3 1845.75   631.8 1843.83   638.4  1841.4
     681 1844.03   730.1 1843.16   736.6 1845.59   756.3 1859.76   782.4 1868.98
   821.7 1876.07   857.8 1880.72   870.8 1883.89  887.661884.091   921.41890.002
   978.9 1900.56    1028  1912.8  1067.3 1928.68  1155.7 1972.39  1191.7 1988.08
#Mann= 7 ,-1 , 0
       0     .12       0  347.75    .016       0  381.49     .12       0
   631.8     .04       0     681     .12       0  887.66    .016       0
   921.4     .12       0
#XS Ineff= 2 , 0
          392.04 1846.69
Permanent Ineff=
       F       F
Bank Sta=631.8,681
XS Rating Curve= 0 ,0
Exp/Cntr=0.3,0.1

Type RM Length L Ch R = 1 ,10342   ,476.1,476.1,476.1
XS GIS Cut Line= 2
     2154491.594      273657.189     2155542.661      273222.059
#Sta/Elev= 30
       0 1956.85      59 1931.79   131.1 1894.84   186.9  1870.6     236 1858.18
   275.4 1844.16  298.921842.958  334.141836.439   357.3 1840.25   373.7 1837.92
   419.6 1836.36   439.3 1839.94   547.5 1840.52     554    1839   560.6 1835.96
   570.4 1835.47   580.1 1835.66   593.4 1839.05   622.9 1840.25     695 1838.47
   731.1 1840.57   750.7  1838.1   780.2 1838.66   790.1 1841.73   816.3 1860.47
  845.64 1867.45     872 1867.77  877.611870.211  1032.7 1896.56  1137.6  1932.3
#Mann= 7 ,-1 , 0
       0     .12       0  298.92    .016       0  334.14     .12       0
     554     .04       0   593.4     .12       0  845.64    .016       0
  877.61     .12       0
#XS Ineff= 2 , 0
          356.79 1841.38
Permanent Ineff=
       F       F
Bank Sta=554,593.4
XS Rating Curve= 0 ,0
Exp/Cntr=0.3,0.1

Type RM Length L Ch R = 1 ,9866    ,665.4,665.4,665.4
XS GIS Cut Line= 2
     2154656.506      273897.603     2155616.176      273549.896
#Sta/Elev= 30
       0 1919.15    39.3 1907.48   104.7 1876.87   134.1 1865.57     193 1851.44
  247.191843.661  278.611840.732   284.6 1838.24   327.2 1834.02   402.4 1837.18
   467.8 1835.71   507.1  1838.9   536.5  1839.3   562.7 1838.03   579.1 1834.73
   664.1 1834.68   693.6 1832.05   703.4 1832.64   709.9 1834.94   729.6 1837.15
   752.4 1857.36   765.5 1864.32  781.161864.509   788.4 1864.29   798.2 1869.56
  812.691873.029     867 1884.17   893.1 1893.48   929.1  1909.7  1020.7 1958.55
#Mann= 7 ,-1 , 0
       0     .12       0  247.19    .016       0  278.61     .12       0
   664.1     .04       0   709.9     .12       0  781.16    .016       0
  812.69     .12       0
Bank Sta=664.1,709.9
XS Rating Curve= 0 ,0
Exp/Cntr=0.3,0.1

Type RM Length L Ch R = 1 ,9201    ,420.4,420.4,420.4
XS GIS Cut Line= 3
     2154845.261       274161.86     2155310.195      274233.388
     2155763.207       274136.03
#Sta/Elev= 30
       0    1852    71.9 1850.49   120.9 1847.24   163.3  1846.4   215.6 1842.37
  253.331842.106   313.11838.415   356.1 1840.02   382.2 1837.66   411.6 1831.04
   476.9 1831.64   496.5 1827.08   555.2 1826.76   568.3    1830   578.1 1827.52
   594.4 1828.25   610.7  1825.5   630.3 1826.06  635.25  1828.1   646.6  1840.9
   653.1 1845.52  673.911846.379   679.2 1846.28   692.3 1855.28  704.121857.909
   744.5 1867.05   819.6 1890.77   855.4 1900.53   884.8 1904.95   933.8 1902.17
#Mann= 7 ,-1 , 0
       0     .12       0  253.33    .016       0   313.1     .12       0
   594.4     .04       0  635.25     .12       0  673.91    .016       0
  704.12     .12       0
#XS Ineff= 2 , 0
          478.26 1834.42
Permanent Ineff=
       F       F
Bank Sta=594.4,635.25
XS Rating Curve= 0 ,0
Exp/Cntr=0.3,0.1

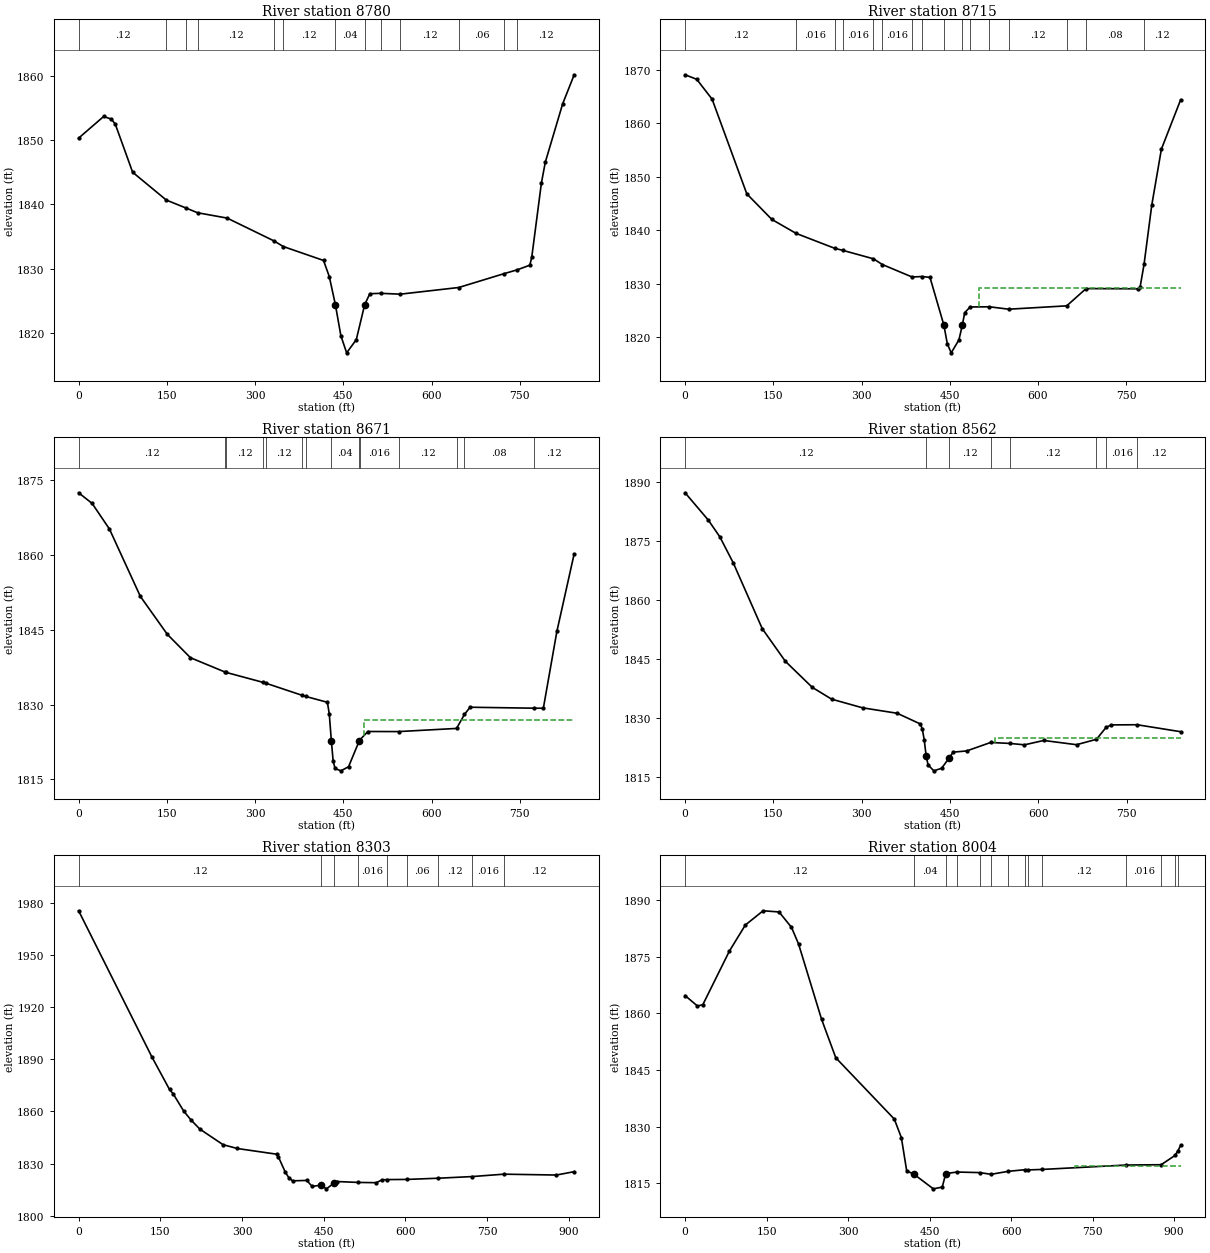
Type RM Length L Ch R = 1 ,8780    ,65.4,65.4,65.4
XS GIS Cut Line= 2
     2154903.693      274366.863     2155654.561      274748.807
#Sta/Elev= 30
       0 1850.34    42.6 1853.72    55.7  1853.3    62.3 1852.52    91.8 1845.02
  149.061840.678   182.21839.451  202.14  1838.7   252.4 1837.87  332.451834.293
  347.891833.431   416.3 1831.26   426.1 1828.75  436.511824.343   445.8 1819.52
   455.6 1816.85     472  1818.9  486.191824.343     495 1826.07  513.581826.133
  546.71    1826  646.131827.041  723.391829.205  745.541829.796     767 1830.52
   770.3 1831.77   786.7 1843.34   793.3 1846.58   822.8 1855.68   842.4 1860.22
#Mann= 13 ,-1 , 0
       0     .12       0  149.06    .016       0   182.2     .06       0
  202.14     .12       0  332.45     .06       0  347.89     .12       0
  436.51     .04       0  486.19     .12       0  513.58    .016       0
  546.71     .12       0  646.13     .06       0  723.39     .08       0
  745.54     .12       0
Bank Sta=436.51,486.19
XS Rating Curve= 0 ,0
Exp/Cntr=0.5,0.3

Type RM Length L Ch R = 1 ,8715    ,44,44,44
XS GIS Cut Line= 2
     2154866.801      274429.797     2155624.179       274798.72
#Sta/Elev= 30
       0 1869.04    19.7  1868.2    45.9 1864.49   104.9  1846.8   147.5 1842.02
  188.821839.412  254.531836.622  267.921836.254  320.23 1834.67  335.381833.599
  385.94 1831.27  402.831831.365   416.3  1831.2  439.871822.306   445.8 1818.78
   452.4 1817.11   465.5 1819.53  471.33 1822.31   475.3  1824.6   484.51825.677
  517.35 1825.71  550.21 1825.26  648.771825.887  681.621829.108   770.3 1829.07
   773.6 1829.46  780.181833.625   793.3 1844.68   809.7 1855.16   842.4 1864.37
#Mann= 16 ,-1 , 0
       0     .12       0  188.82    .016       0  254.53     .12       0
  267.92    .016       0  320.23     .06       0  335.38    .016       0
  385.94     .12       0  402.83    .016       0  439.87     .04       0
  471.33    .016       0   484.5     .12       0  517.35    .016       0
  550.21     .12       0  648.77     .06       0  681.62     .08       0
  780.18     .12       0
#XS Ineff= 2 , 0
                             500          1829.2
Permanent Ineff=
       F       F
Bank Sta=439.87,471.33
XS Rating Curve= 0 ,0
Exp/Cntr=0.5,0.3

Type RM Length L Ch R = 1 ,8671    ,108.9,108.9,108.9
XS GIS Cut Line= 2
     2154842.929      274466.689     2155600.308      274835.613
#Sta/Elev= 30
       0 1872.43      23 1870.29    52.4 1865.16   104.9 1851.68   150.8 1844.07
   190.1 1839.39  248.221836.551  251.121836.433  313.93 1834.44  318.571834.272
  379.641831.869  386.031831.636   422.9 1830.46   426.1 1828.12  429.69 1822.64
   432.7 1818.64     436  1817.2   445.8 1816.73   458.9 1817.56  476.711822.635
   478.21822.946   491.7 1824.61   543.91824.593  642.461825.226  655.861828.019
   665.4 1829.47  773.881829.281     790 1829.27     813 1844.66   842.4  1860.2
#Mann= 14 ,-1 , 0
       0     .12       0  248.22    .016       0  251.12     .12       0
  313.93    .016       0  318.57     .12       0  379.64    .016       0
  386.03     .12       0  429.69     .04       0  476.71     .12       0
   478.2    .016       0   543.9     .12       0  642.46     .06       0
  655.86     .08       0  773.88     .12       0
#XS Ineff= 2 , 0
                          484.41         1826.88
Permanent Ineff=
       F       F
Bank Sta=429.69,476.71
XS Rating Curve= 0 ,0
Exp/Cntr=0.5,0.3

Type RM Length L Ch R = 1 ,8562    ,258.9,258.9,258.9
XS GIS Cut Line= 2
     2154803.867      274573.026       2155564.5      274933.269
#Sta/Elev= 30
       0 1887.37    39.3 1880.44      59 1876.16    81.9  1869.5     131  1852.8
   170.3 1844.48   216.1 1837.84   248.9 1834.85   301.3 1832.65   360.2 1831.26
   399.5 1828.54   402.8 1827.28   406.1 1824.52   409.4 1820.41   412.6 1818.15
   422.4 1816.61   435.6 1817.26   448.6  1819.9   455.2 1821.37   478.1 1821.67
   518.91823.828  551.581823.585   576.4 1823.23   609.1 1824.34   664.8 1823.26
   698.61824.633  714.981827.665   723.7  1828.3  767.621828.342   841.6 1826.57
#Mann= 8 ,-1 , 0
       0     .12       0   409.4     .04       0   448.6     .12       0
   518.9    .016       0  551.58     .12       0   698.6     .06       0
  714.98    .016       0  767.62     .12       0
#XS Ineff= 2 , 0
                          526.73         1824.92
Permanent Ineff=
       F       F
Bank Sta=409.4,448.6
XS Rating Curve= 0 ,0
Exp/Cntr=0.3,0.1

Type RM Length L Ch R = 1 ,8303    ,299.4,299.4,299.4
XS GIS Cut Line= 3
     2154680.298       274849.05     2155109.441      275000.258
     2155538.694      275151.139
#Sta/Elev= 30
       0 1975.29   134.2  1891.5   166.9  1872.6   173.5 1870.16   193.1 1860.12
   206.2 1855.14   222.6 1849.83   265.2 1840.89   291.3 1838.69   363.4 1835.43
   366.6 1834.05   379.7 1824.94   386.3 1821.81   392.8 1820.11     419 1820.34
   428.8 1816.89   445.2 1817.66     455 1815.51   468.1  1818.6   474.6  1819.7
  513.681819.193   546.7 1819.04   556.5  1820.6  565.551820.824  602.76 1820.92
  659.481821.602  722.091822.551  780.941823.937   877.3 1823.44     910 1825.37
#Mann= 9 ,-1 , 0
       0     .12       0   445.2     .04       0   468.1     .12       0
  513.68    .016       0  565.55     .12       0  602.76     .06       0
  659.48     .12       0  722.09    .016       0  780.94     .12       0
Bank Sta=445.2,468.1
XS Rating Curve= 0 ,0
Exp/Cntr=0.3,0.1

Type RM Length L Ch R = 1 ,8004    ,411.2,411.2,411.2
XS GIS Cut Line= 3
     2154598.541      275122.199     2155024.516      275287.101
     2155454.368      275436.611
#Sta/Elev= 30
       0 1864.74    22.8 1861.97    32.6 1862.32    81.6 1876.55   110.9 1883.43
   143.6  1887.2   172.9 1886.89   195.8 1882.81   208.8  1878.4   251.2 1858.43
   277.3 1848.26     385 1832.02     398  1827.1   407.8 1818.29   420.9 1817.44
   456.8 1813.54   473.2    1814   479.7 1817.58  500.741817.993  541.941817.839
  563.281817.394  594.551818.175  625.831818.615  631.871818.556   657.11818.679
  811.731819.846     8761819.928  901.651822.388  907.271823.693   911.9 1825.07
#Mann= 14 ,-1 , 0
       0     .12       0   420.9     .04       0   479.7     .12       0
  500.74    .016       0  541.94     .06       0  563.28     .08       0
  594.55    .016       0  625.83     .12       0  631.87     .08       0
   657.1     .12       0  811.73    .016       0     876     .12       0
  901.65    .016       0  907.27     .12       0
#XS Ineff= 2 , 0
                          717.41         1819.46
Permanent Ineff=
       F       F
Bank Sta=420.9,479.7
XS Rating Curve= 0 ,0
Exp/Cntr=0.3,0.1