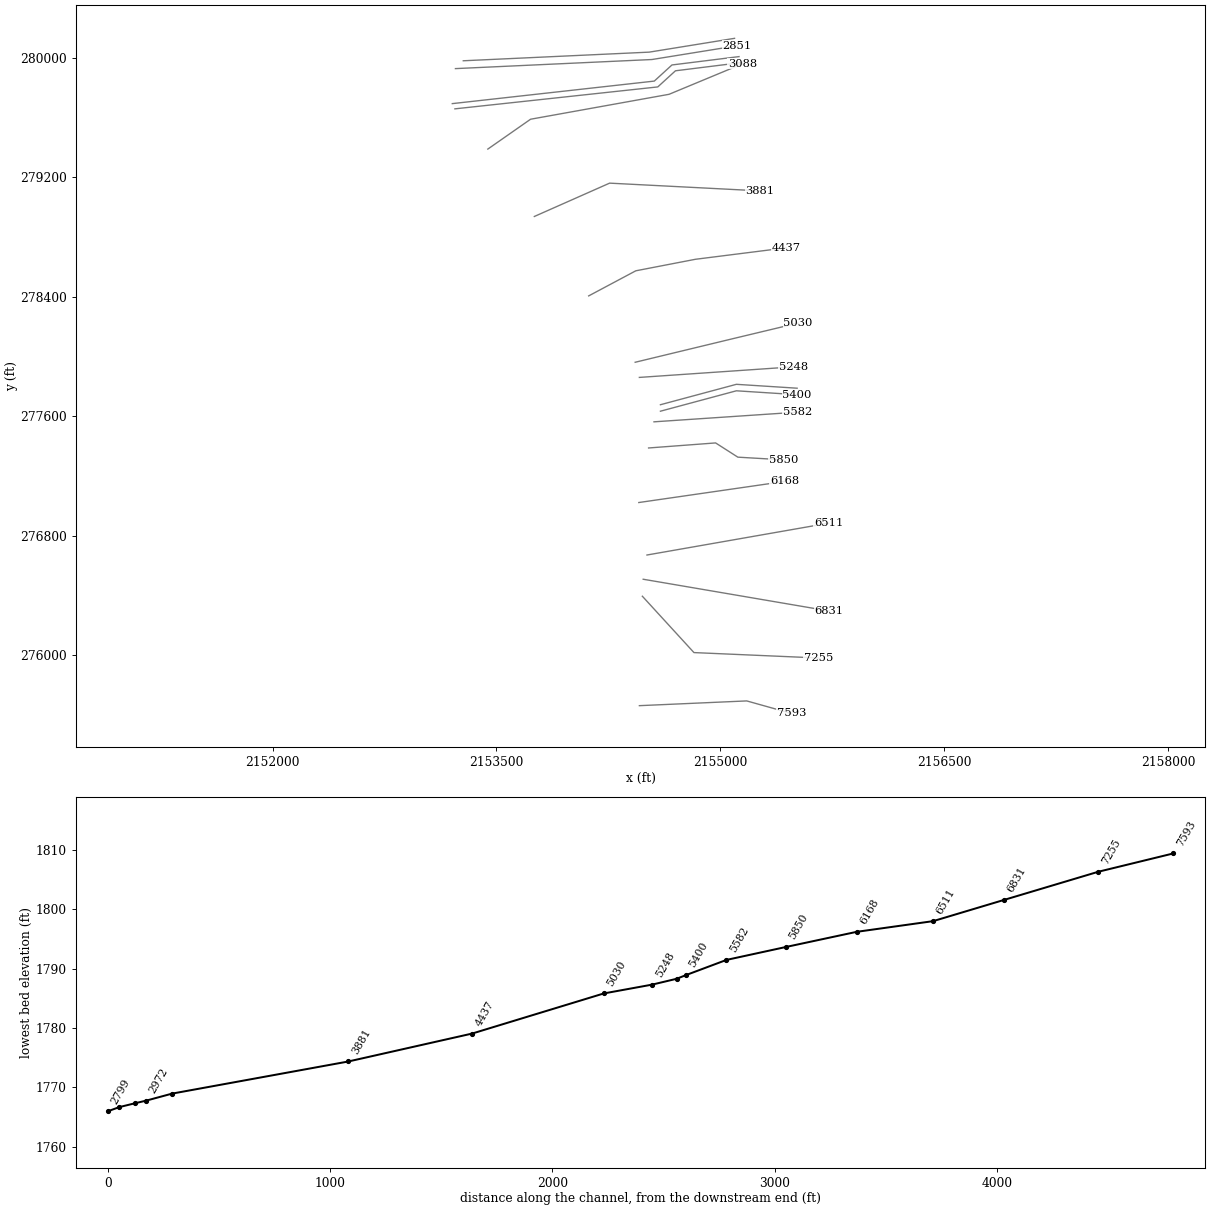
HEC-RAS study HARTSRN.prj: HARTSRN

--- HARTSRN.g01 (geometry) --- (continued)

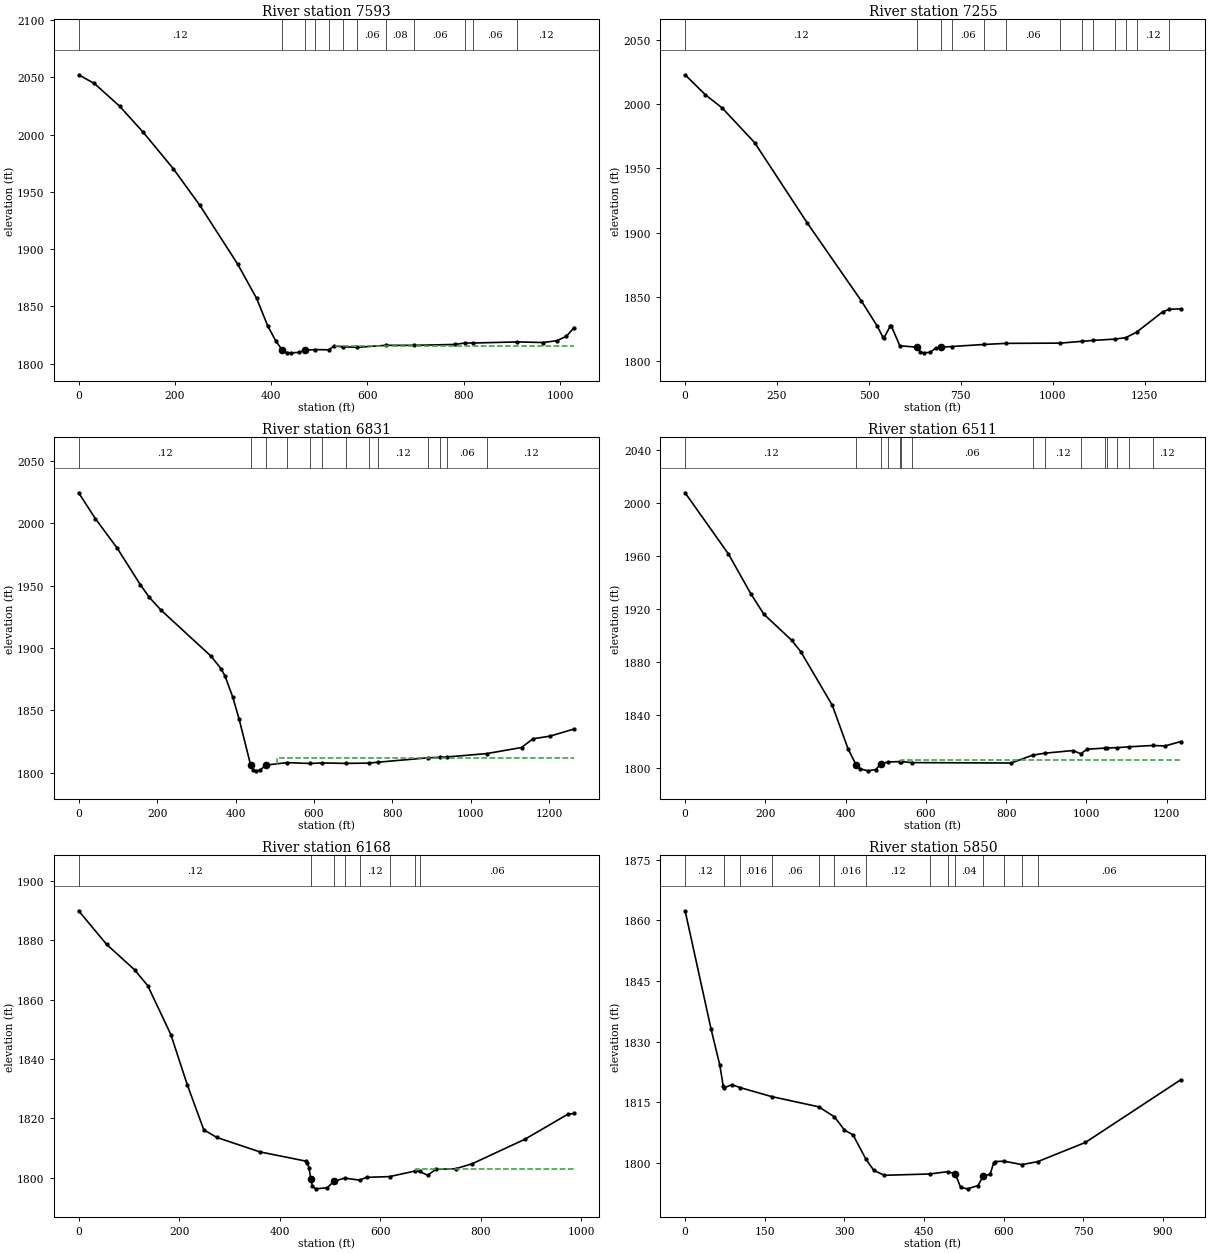
Type RM Length L Ch R = 1 ,7593    ,338,338,338
XS GIS Cut Line= 3
     2154457.817      275659.979     2155177.073      275691.769
     2155475.107       275608.32
#Sta/Elev= 30
       0 2052.16    32.7 2044.55    85.1 2024.77   134.2 2001.94   196.4 1970.29
     252 1938.05   330.5 1886.76   369.8 1856.86   392.7 1833.08   409.1  1820.1
   422.2 1812.26     432 1809.64   441.8  1809.4   458.2 1809.81   471.2  1811.8
  490.521812.199  520.091812.058   530.2 1815.31  549.661814.657  579.221814.231
  638.351815.969  697.481815.946   781.9 1816.72  802.441818.024  819.331817.975
  911.35 1818.93   964.3 1818.41   993.6    1820  1013.2 1823.82  1029.4 1831.52
#Mann= 12 ,-1 , 0
       0     .12       0   422.2     .04       0   471.2     .12       0
  490.52     .06       0  520.09     .12       0  549.66    .016       0
  579.22     .06       0  638.35     .08       0  697.48     .06       0
  802.44     .12       0  819.33     .06       0  911.35     .12       0
#XS Ineff= 2 , 0
                          532.14         1815.49
Permanent Ineff=
       F       F
Bank Sta=422.2,471.2
XS Rating Curve= 0 ,0
Exp/Cntr=0.3,0.1

Type RM Length L Ch R = 1 ,7255    ,423.7,423.7,423.7
XS GIS Cut Line= 3
     2154477.686      276393.143     2154823.405      276015.633
      2155658.38      275979.363
#Sta/Elev= 30
       0 2022.85    55.4 2007.22   101.1 1996.97   189.1    1970   332.6  1907.3
   479.3 1846.77   521.7 1827.52   538.1 1818.57   541.4 1818.19   557.8  1827.1
   561.1 1827.06     584 1811.82  630.85  1810.7   639.7  1806.8   649.6 1806.31
   665.9  1806.7   682.3 1810.07   697.3  1810.7  725.141811.234  813.841812.848
  872.971813.689 1020.791813.883 1079.921815.299 1109.481815.976 1168.611817.013
 1198.181818.117 1227.741822.351  1298.5 1838.19 1316.441840.201  1347.7 1840.56
#Mann= 13 ,-1 , 0
       0     .12       0  630.85     .04       0   697.3    .016       0
  725.14     .06       0  813.84     .12       0  872.97     .06       0
 1020.79     .12       0 1079.92     .06       0 1109.48     .12       0
 1168.61    .016       0 1198.18     .06       0 1227.74     .12       0
 1316.44     .08       0
Bank Sta=630.85,697.3
XS Rating Curve= 0 ,0
Exp/Cntr=0.3,0.1

Type RM Length L Ch R = 1 ,6831    ,319.5,319.5,319.5
XS GIS Cut Line= 2
     2154483.226      276507.058     2155728.398       276294.44
#Sta/Elev= 30
       0 2024.28    42.5 2003.62    98.2 1979.99   157.1 1950.76     180 1940.63
   209.4 1930.48   337.1 1893.52   363.2 1883.31   373.1  1877.5   392.7 1860.82
   409.1 1843.03   438.5 1806.16   445.1 1801.97   451.6 1801.57   461.8 1801.97
  477.591806.157  531.241808.174   588.91807.457  621.131807.896  681.061807.528
  740.991807.794  764.311808.532  890.821812.001  920.781812.404  939.721812.711
 1040.641815.389    1129 1820.26  1158.5 1827.27    1201 1829.32  1263.2 1835.09
#Mann= 13 ,-1 , 0
       0     .12       0   438.5     .04       0  477.59    .016       0
  531.24     .06       0   588.9     .12       0  621.13     .06       0
  681.06     .12       0  740.99     .06       0  764.31     .12       0
  890.82     .06       0  920.78     .12       0  939.72     .06       0
 1040.64     .12       0
#XS Ineff= 2 , 0
                          506.39         1811.81
Permanent Ineff=
       F       F
Bank Sta=438.5,477.59
XS Rating Curve= 0 ,0
Exp/Cntr=0.3,0.1

Type RM Length L Ch R = 1 ,6511    ,343.7,343.7,343.7
XS GIS Cut Line= 2
     2154508.538       276669.36     2155724.897      276882.584
#Sta/Elev= 30
       0 2007.64   108.1 1961.44   163.8 1931.48   196.5 1916.02   265.3 1896.52
   288.2 1887.87   366.9 1847.37   406.2 1814.48   425.8 1802.71   435.7 1799.57
   455.3 1797.99     475 1798.97   488.1 1803.34  505.931804.645  535.911804.983
  538.711804.958   565.91804.187   812.4 1803.89  865.771809.773  895.761811.273
   966.3 1813.29  985.721810.913  1002.3 1814.29 1045.691815.141  1052.11815.302
 1075.68 1815.44 1105.661816.095 1165.641817.114  1195.6 1816.72  1234.9 1820.04
#Mann= 15 ,-1 , 0
       0     .12       0   425.8     .04       0   488.1     .12       0
  505.93    .016       0  535.91     .06       0  538.71     .12       0
   565.9     .06       0  865.77    .016       0  895.76     .12       0
  985.72    .016       0 1045.69     .12       0  1052.1     .06       0
 1075.68     .12       0 1105.66     .06       0 1165.64     .12       0
#XS Ineff= 2 , 0
                          537.86         1806.43
Permanent Ineff=
       F       F
Bank Sta=425.8,488.1
XS Rating Curve= 0 ,0
Exp/Cntr=0.3,0.1

Type RM Length L Ch R = 1 ,6168    ,317.9,317.9,317.9
XS GIS Cut Line= 2
     2154453.843      277021.002     2155429.408      277162.071
#Sta/Elev= 30
       0 1889.98    55.7 1878.63   111.3 1870.07   137.5 1864.71   183.4 1848.23
   216.1  1831.3   248.9 1816.11   275.1 1813.51   360.2 1808.67   451.9 1805.54
   455.2 1805.03   458.5 1803.06   461.8 1799.53     465  1797.1   471.6 1796.19
   494.5 1796.56   507.6  1798.7  528.911799.816  558.75 1799.13   573.1 1800.06
  618.441800.318  669.531802.209  678.131802.046   694.3 1800.77   710.6 1802.77
   749.9 1802.97   782.7 1804.64   887.5  1812.9   972.6 1821.31   985.7 1821.63
#Mann= 8 ,-1 , 0
       0     .12       0   461.8     .04       0   507.6     .12       0
  528.91    .016       0  558.75     .12       0  618.44    .016       0
  669.53     .12       0  678.13     .06       0
#XS Ineff= 2 , 0
                          671.49         1802.96
Permanent Ineff=
       F       F
Bank Sta=461.8,507.6
XS Rating Curve= 0 ,0
Exp/Cntr=0.3,0.1

Type RM Length L Ch R = 1 ,5850    ,267.8,267.8,267.8
XS GIS Cut Line= 4
      2154519.41       277386.59     2154968.449      277420.368
     2155117.466      277324.997     2155423.448      277307.115
#Sta/Elev= 30
       0 1862.39      49 1833.11    65.3 1824.27    71.8 1819.14   74.111818.642
    88.1  1819.4  103.731818.678  162.971816.454  251.831813.918  281.451811.435
   300.2 1808.19   316.5 1806.96  341.051800.896   355.7 1798.18   375.3 1796.99
   460.81797.316  495.871797.904   509.3 1797.29   519.1    1794   532.2 1793.64
   551.9 1794.45   561.7 1796.78   574.8 1797.26   581.4 1800.07   584.6 1800.39
  601.081800.477  634.751799.634  664.341800.361   754.4 1805.12   933.7 1820.59
#Mann= 14 ,-1 , 0
       0     .12       0   74.11     .06       0  103.73    .016       0
  162.97     .06       0  251.83     .12       0  281.45    .016       0
  341.05     .12       0   460.8    .016       0  495.87     .12       0
   509.3     .04       0   561.7     .12       0  601.08    .016       0
  634.75     .12       0  664.34     .06       0
Bank Sta=509.3,561.7
XS Rating Curve= 0 ,0
Exp/Cntr=0.3,0.1

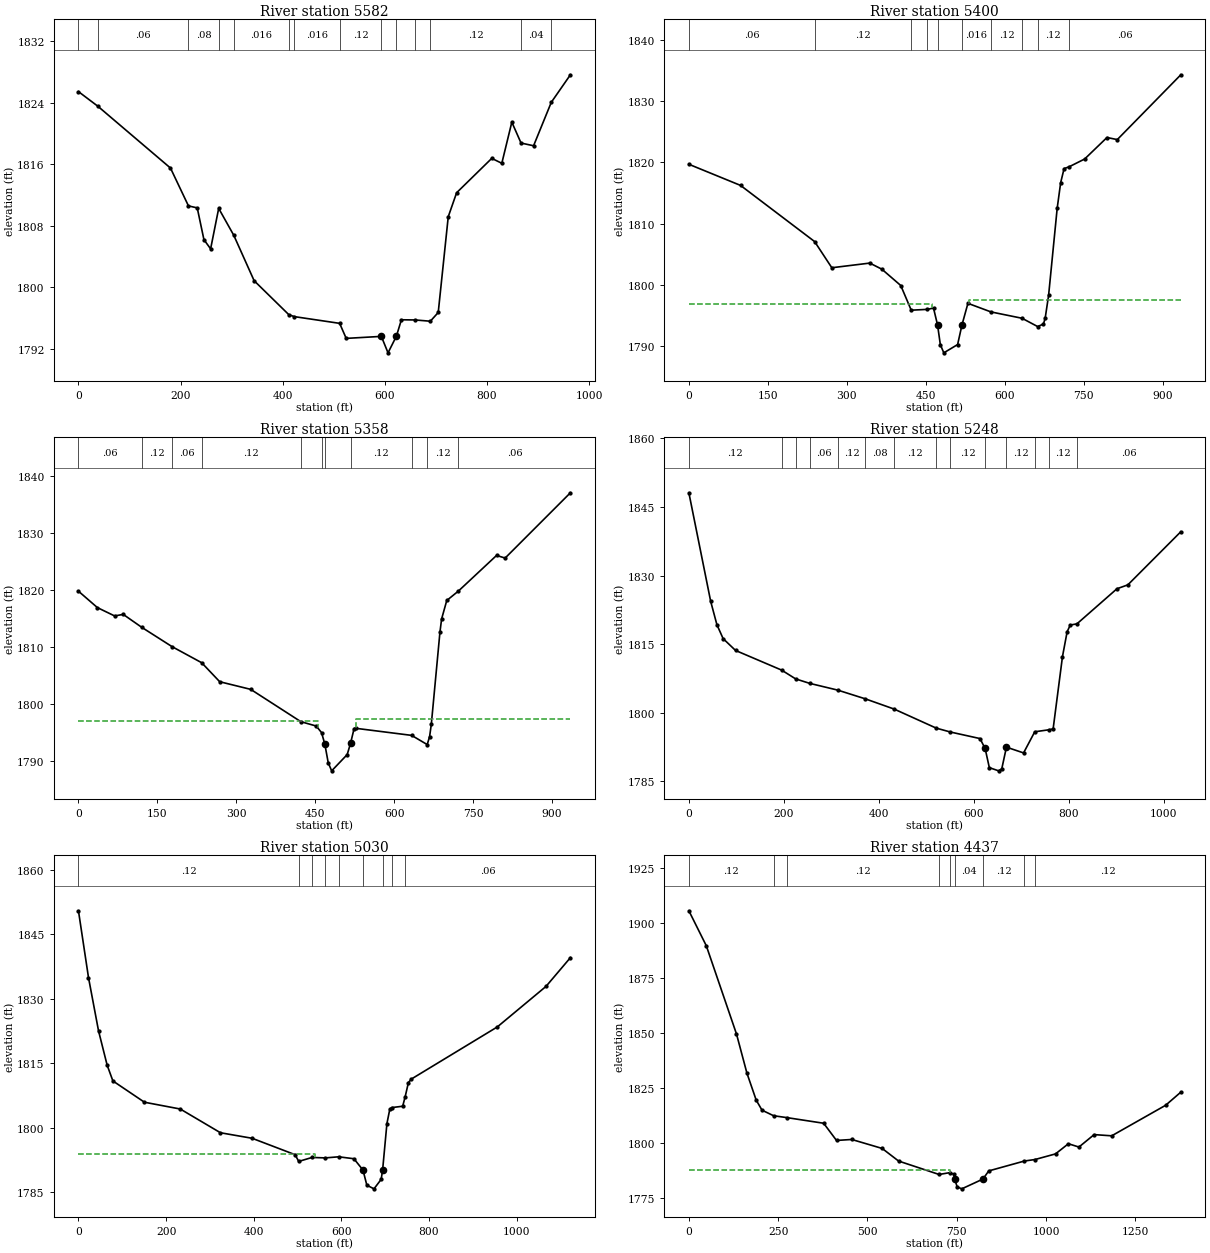
Type RM Length L Ch R = 1 ,5582    ,181.7,181.7,181.7
XS GIS Cut Line= 2
      2154555.61      277561.751     2155516.757      277626.411
#Sta/Elev= 30
       0 1825.43   37.77 1823.54   180.2 1815.49  215.391810.569   232.6 1810.31
   245.7 1806.18   258.8 1804.98   274.61810.246   304.21806.739     344 1800.84
  411.921796.424  422.621796.171  511.431795.295   524.3 1793.34   593.1  1793.6
   606.2 1791.46   622.6 1793.63   632.4 1795.76  659.451795.735  689.051795.571
   704.5 1796.71   724.1 1809.16   740.5 1812.28   809.3 1816.75     829 1816.11
   848.6 1821.46  866.671818.742   891.2 1818.39  925.88 1824.04   963.3 1827.62
#Mann= 14 ,-1 , 0
       0     .12       0   37.77     .06       0  215.39     .08       0
   274.6     .12       0   304.2    .016       0  411.92     .12       0
  422.62    .016       0  511.43     .12       0   593.1     .04       0
   622.6     .12       0  659.45    .016       0  689.05     .12       0
  866.67     .04       0  925.88     .06       0
Bank Sta=593.1,622.6
XS Rating Curve= 0 ,0
Exp/Cntr=0.5,0.3

Type RM Length L Ch R = 1 ,5400    ,42.6,42.6,42.6
XS GIS Cut Line= 3
     2154598.789      277632.922     2155107.686       277769.64
     2155514.587      277743.599
#Sta/Elev= 30
       0 1819.69    98.2 1816.24  238.981807.069   271.6  1802.8   343.7 1803.56
   366.6 1802.57   402.6  1799.9  422.481795.872  453.061796.005   464.8 1796.22
  472.511793.455   477.8 1790.24   484.4 1788.91   510.6 1790.26  518.88 1793.46
   530.2 1796.99  574.031795.589  633.031794.554  662.631793.202   673.7 1793.61
     677 1794.57   683.5  1798.3   699.8 1812.51   706.4 1816.68   712.9 1818.99
  721.821819.253     752 1820.55   794.4 1824.06     814 1823.72   934.7  1834.3
#Mann= 10 ,-1 , 0
       0     .06       0  238.98     .12       0  422.48    .016       0
  453.06     .12       0  472.51     .04       0  518.88    .016       0
  574.03     .12       0  633.03    .016       0  662.63     .12       0
  721.82     .06       0
#XS Ineff= 2 , 0
          461.02 1796.88  532.29         1797.46
Permanent Ineff=
       F       F
Bank Sta=472.51,518.88
XS Rating Curve= 0 ,0
Exp/Cntr=0.5,0.3

Type RM Length L Ch R = 1 ,5358    ,109.9,109.9,109.9
XS GIS Cut Line= 3
     2154598.789      277676.324     2155107.686      277813.043
     2155514.587      277787.002
#Sta/Elev= 30
       0 1819.79      36 1816.91    68.7 1815.45    85.1 1815.72  120.28 1813.45
  177.811810.066  234.141807.242   268.4 1803.91   327.3 1802.57  422.481796.908
   451.7 1796.14  461.881794.989   468.11792.969   474.6 1789.68   481.1 1788.28
   510.6 1791.13   517.1 1793.15   523.7 1795.69   526.9 1795.74  633.03  1794.5
  662.621792.888   667.2 1794.29   670.5  1796.5   686.8 1812.58     690 1814.92
   699.8 1818.16  721.821819.803   794.4 1826.06   810.7  1825.6   934.7 1837.05
#Mann= 11 ,-1 , 0
       0     .06       0  120.28     .12       0  177.81     .06       0
  234.14     .12       0  422.48    .016       0  461.88     .12       0
   468.1     .04       0   517.1     .12       0  633.03    .016       0
  662.62     .12       0  721.82     .06       0
#XS Ineff= 2 , 0
          454.34 1796.98  527.84         1797.36
Permanent Ineff=
       F       F
Bank Sta=468.1,517.1
XS Rating Curve= 0 ,0
Exp/Cntr=0.5,0.3

Type RM Length L Ch R = 1 ,5248    ,217.8,217.8,217.8
XS GIS Cut Line= 2
     2154457.586      277859.323     2155490.716      277930.231
#Sta/Elev= 30
       0 1848.12    45.9 1824.38      59 1819.27    72.1 1816.22    98.3 1813.63
  195.221809.335  224.831807.408  254.441806.431  313.65 1804.95  371.461803.047
  432.071800.813  520.891796.637   550.51795.793   612.8 1794.36  623.661792.187
   632.5    1788   652.1  1787.3   658.7 1787.74   668.5 1792.48   704.6 1791.22
  728.131795.845  757.741796.277   766.8 1796.46   786.5  1812.3   796.3 1817.73
   802.9 1819.19  816.951819.453   901.2 1827.13   924.1 1827.98  1035.6  1839.6
#Mann= 14 ,-1 , 0
       0     .12       0  195.22     .06       0  224.83     .12       0
  254.44     .06       0  313.65     .12       0  371.46     .08       0
  432.07     .12       0  520.89    .016       0   550.5     .12       0
  623.66     .04       0   668.5     .12       0  728.13    .016       0
  757.74     .12       0  816.95     .06       0
Bank Sta=623.66,668.5
XS Rating Curve= 0 ,0
Exp/Cntr=0.3,0.1

Type RM Length L Ch R = 1 ,5030    ,592.6,592.6,592.6
XS GIS Cut Line= 3
     2154429.579      277960.848     2155082.001      278118.347
     2155521.011      278223.413
#Sta/Elev= 30
       0 1850.47    22.9 1834.95    45.8 1822.56    65.5 1814.56    78.6  1810.9
   150.6 1805.95   232.4 1804.37   324.1 1798.85   396.2 1797.57   494.4 1793.75
  502.631792.183  533.011793.109   563.41793.005  593.78 1793.26   628.6 1792.81
  649.261790.181   658.1 1786.66   674.4 1785.81   690.8 1788.02  694.07 1790.18
   703.9 1800.99   710.4 1804.29   715.31804.708   739.9 1805.02  745.67 1807.28
   752.9  1810.5   759.5 1811.33   955.8 1823.46    1067 1832.89  1122.6 1839.57
#Mann= 9 ,-1 , 0
       0     .12       0  502.63    .016       0  533.01     .12       0
   563.4     .06       0  593.78     .12       0  649.26     .04       0
  694.07     .12       0   715.3    .016       0  745.67     .06       0
#XS Ineff= 2 , 0
          539.87 1793.89
Permanent Ineff=
       F       F
Bank Sta=649.26,694.07
XS Rating Curve= 0 ,0
Exp/Cntr=0.3,0.1

Type RM Length L Ch R = 1 ,4437    ,556.4,556.4,556.4
XS GIS Cut Line= 4
     2154118.003      278405.457     2154433.732      278573.626
     2154832.863      278650.745     2155441.327      278727.536
#Sta/Elev= 30
       0 1905.39    48.8 1889.51   133.3 1849.43   162.6  1831.6   188.6 1819.33
   204.9 1814.78  237.251812.266  274.571811.406   377.4 1808.85   413.4 1801.04
   456.1 1801.48   541.3  1797.4   587.2 1791.68  700.671785.576  730.751786.412
   741.3 1785.74  744.531783.489   751.1 1779.96   764.2 1779.05   823.41783.491
   839.7  1787.2  939.491791.686  969.261792.374  1026.6 1794.92  1062.7 1799.54
  1092.2 1798.04  1134.8 1803.69    1184 1803.14  1334.9 1817.01  1377.5 1822.98
#Mann= 9 ,-1 , 0
       0     .12       0  237.25     .06       0  274.57     .12       0
  700.67    .016       0  730.75     .12       0  744.53     .04       0
   823.4     .12       0  939.49    .016       0  969.26     .12       0
#XS Ineff= 2 , 0
          730.02 1787.54
Permanent Ineff=
       F       F
Bank Sta=744.53,823.4
XS Rating Curve= 0 ,0
Exp/Cntr=0.3,0.1

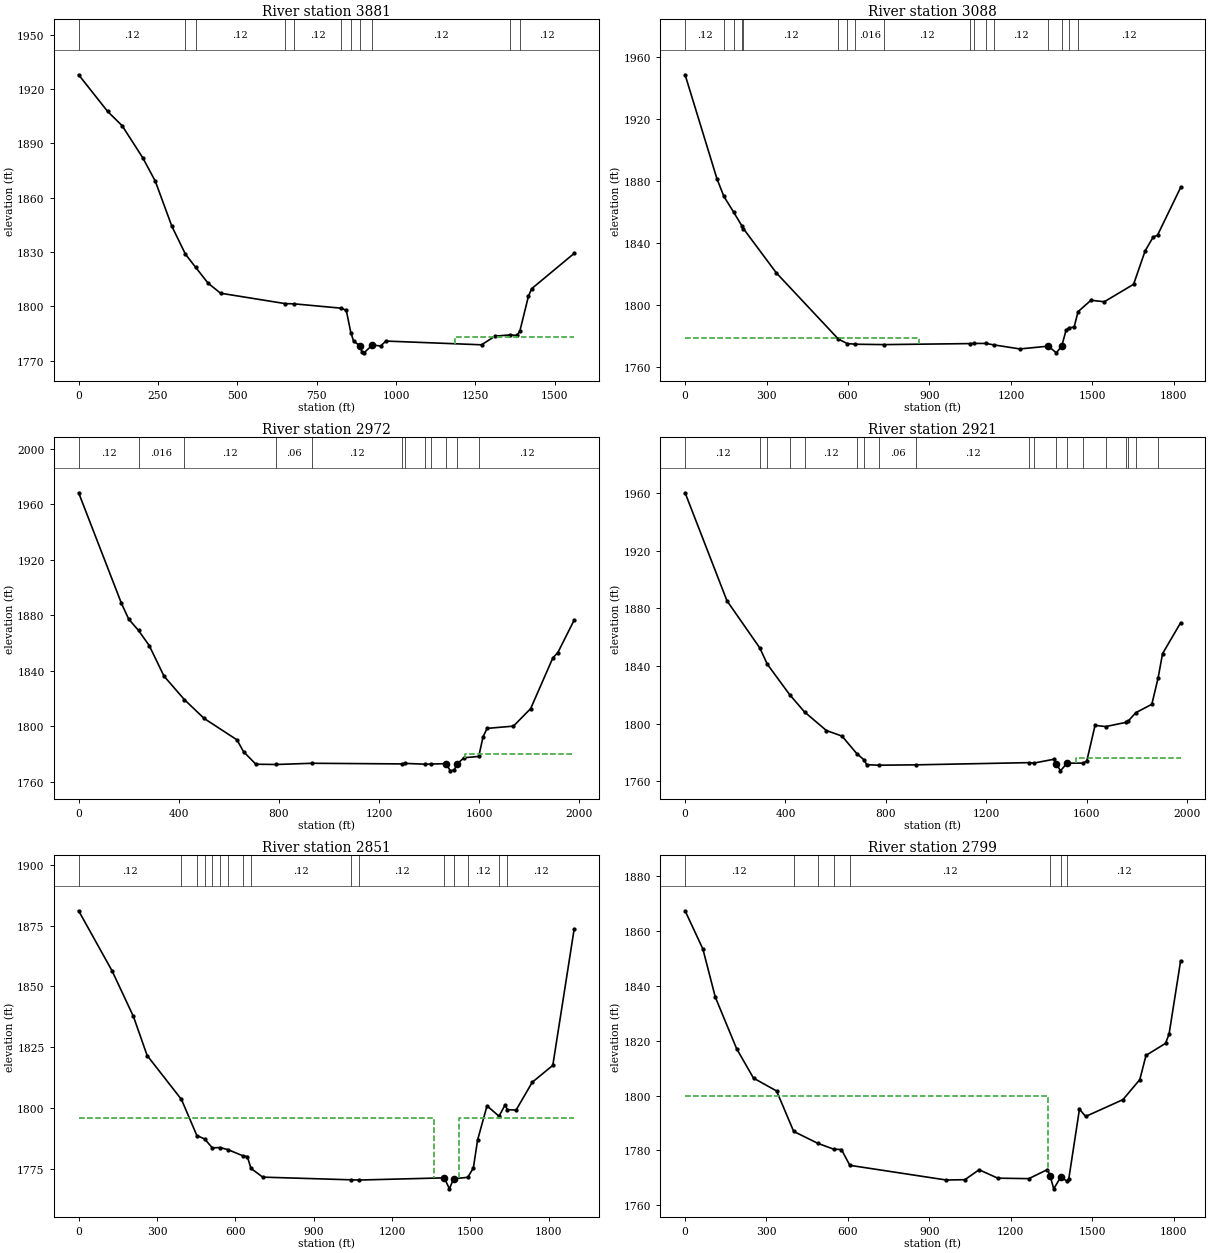
Type RM Length L Ch R = 1 ,3881    ,792.7,792.7,792.7
XS GIS Cut Line= 3
     2153753.914      278937.588     2154258.202      279160.959
     2155266.284       279109.13
#Sta/Elev= 30
       0 1927.88    91.4 1907.63   137.1 1899.75   202.3 1881.97   241.5 1869.13
   293.7 1844.22  336.451828.829  368.761821.523     408 1812.78   447.1 1807.27
  650.38 1801.54  679.951801.387  827.83 1798.99   843.2 1797.77  857.411785.552
   866.2  1780.8   885.8 1778.31   892.4 1774.78   898.9 1774.35   925.2 1778.67
   951.4 1778.14   967.8 1780.85  1269.3 1778.79  1311.9 1783.57  1360.21784.278
  1380.7 1783.94 1389.781786.278  1416.8 1805.49  1426.6  1809.7    1561 1829.27
#Mann= 11 ,-1 , 0
       0     .12       0  336.45    .016       0  368.76     .12       0
  650.38    .016       0  679.95     .12       0  827.83    .016       0
  857.41     .12       0   885.8     .04       0   925.2     .12       0
  1360.2    .016       0 1389.78     .12       0
#XS Ineff= 2 , 0
                         1186.64         1783.15
Permanent Ineff=
       F       F
Bank Sta=885.8,925.2
XS Rating Curve= 0 ,0
Exp/Cntr=0.3,0.1

Type RM Length L Ch R = 1 ,3088    ,116.3,116.3,116.3
XS GIS Cut Line= 4
     2153442.337      279389.198       2153728.7       279589.18
     2154656.514      279756.186     2155148.702      279960.613
#Sta/Elev= 30
       0 1948.38   117.5 1881.19  142.771869.916  178.791859.734  209.59 1850.74
  214.821849.075   336.2 1820.49  564.851777.749   597.4 1774.91  627.411774.499
  731.641774.252 1047.561774.906 1065.22 1775.02 1107.581774.998  1137.6 1774.06
  1233.1 1771.46  1337.8 1773.25  1367.2 1768.94  1386.8 1773.17  1403.2 1783.61
 1415.291785.171  1432.6  1785.5 1447.28 1795.52  1494.7 1802.88  1543.8 1801.91
  1651.7 1813.17  1694.2 1834.71  1723.6 1843.61    1740 1844.91    1825 1875.67
#Mann= 17 ,-1 , 0
       0     .12       0  142.77    .016       0  178.79     .12       0
  209.59    .016       0  214.82     .12       0  564.85    .016       0
   597.4     .12       0  627.41    .016       0  731.64     .12       0
 1047.56    .016       0 1065.22     .12       0 1107.58    .016       0
  1137.6     .12       0  1337.8     .04       0  1386.8     .12       0
 1415.29    .016       0 1447.28     .12       0
#XS Ineff= 2 , 0
          861.92 1778.62
Permanent Ineff=
       F       F
Bank Sta=1337.8,1386.8
XS Rating Curve= 0 ,0
Exp/Cntr=0.3,0.1

Type RM Length L Ch R = 1 ,2972    ,51.1,51.1,51.1
XS GIS Cut Line= 4
     2153221.783      279658.764     2154580.993      279805.665
     2154699.483      279913.738     2155148.702      279969.727
#Sta/Elev= 30
       0 1968.24   170.5 1888.78     200 1877.17   239.3 1868.96     282 1858.12
     341 1836.09   422.9 1819.04   501.6 1805.53   632.8 1790.09     659 1781.57
   708.2 1772.53   790.1 1772.34  933.721773.212 1290.221772.754  1304.8 1773.12
 1383.581772.559 1409.421772.662  1468.6 1772.97    1485 1767.76  1501.3 1768.36
  1511.1 1772.62  1540.6 1777.23 1598.921778.122  1616.1 1792.35  1632.5 1798.38
  1737.4 1799.99  1806.3 1812.62  1894.9 1849.18  1914.6 1852.93  1980.2 1876.44
#Mann= 12 ,-1 , 0
       0     .12       0   239.3    .016       0   422.9     .12       0
   790.1     .06       0  933.72     .12       0 1290.22    .016       0
  1304.8    .016       0 1383.58     .12       0 1409.42    .016       0
  1468.6     .04       0  1511.1    .016       0 1598.92     .12       0
#XS Ineff= 2 , 0
                         1545.66         1779.74
Permanent Ineff=
       F       F
Bank Sta=1468.6,1511.1
XS Rating Curve= 0 ,0
Exp/Cntr=0.3,0.1

Type RM Length L Ch R = 1 ,2921    ,69.8,69.8,69.8
XS GIS Cut Line= 4
     2153204.279      279693.773     2154557.556      279844.727
     2154676.046        279952.8     2155125.264       280008.79
#Sta/Elev= 30
       0 1960.11   166.9 1885.22  297.851852.478  327.571841.272  416.73 1820.12
  476.171808.102     563 1795.27   625.2 1791.41  684.211779.252  713.931774.787
   723.4 1771.57  773.371771.208  921.97 1771.48 1369.861772.992 1389.821772.677
  1469.7 1775.36 1479.04 1772.35  1495.9 1767.31 1521.831772.591 1587.321772.687
  1600.8  1774.2  1633.6 1798.82 1676.611798.013 1757.091800.933 1765.911801.828
 1795.671807.584  1859.9 1813.46 1884.971831.752  1902.6 1848.56  1974.7    1870
#Mann= 19 ,-1 , 0
       0     .12       0  297.85    .016       0  327.57     .12       0
  416.73    .016       0  476.17     .12       0  684.21    .016       0
  713.93     .12       0  773.37     .06       0  921.97     .12       0
 1369.86    .016       0 1389.82     .12       0 1479.04     .04       0
 1521.83    .016       0 1587.32     .12       0 1676.61     .06       0
 1757.09     .08       0 1765.91     .06       0 1795.67     .08       0
 1884.97     .12       0
#XS Ineff= 2 , 0
                         1558.17          1776.5
Permanent Ineff=
       F       F
Bank Sta=1479.04,1521.83
XS Rating Curve= 0 ,0
Exp/Cntr=0.3,0.1

Type RM Length L Ch R = 1 ,2851    ,51.8,51.8,51.8
XS GIS Cut Line= 3
     2153225.284       279928.33     2154541.931      279989.259
     2155113.546      280081.706
#Sta/Elev= 30
       0  1881.1   127.9  1856.4   209.8  1837.6   262.3 1821.54  393.571803.462
   452.71788.594  482.271787.214  511.841783.527  541.411783.667  570.981782.816
  630.111780.222   645.9 1779.96  659.68 1775.09   704.9 1771.49 1044.071770.382
 1073.641770.295  1399.8 1771.19  1419.5 1766.67  1435.8 1770.84 1489.611771.397
  1511.1 1775.23  1527.4 1786.79  1563.4 1800.84 1609.291796.554  1632.1 1801.09
 1641.771799.256  1674.6 1799.07  1736.8 1810.56  1815.3 1817.48  1897.1 1873.58
#Mann= 16 ,-1 , 0
       0     .12       0  393.57    .016       0   452.7     .06       0
  482.27    .016       0  511.84     .12       0  541.41     .06       0
  570.98     .12       0  630.11    .016       0  659.68     .12       0
 1044.07     .06       0 1073.64     .12       0  1399.8     .04       0
  1435.8    .016       0 1489.61     .12       0 1609.29     .08       0
 1641.77     .12       0
#XS Ineff= 2 , 0
          1360.8 1795.71 1454.34          1795.9
Permanent Ineff=
       F       F
Bank Sta=1399.8,1435.8
XS Rating Curve= 0 ,0
Exp/Cntr=0.5,0.3

Type RM Length L Ch R = 1 ,2799    ,234.5,234.5,234.5
XS GIS Cut Line= 3
     2153277.797      279980.843     2154523.702      280038.738
     2155095.316      280131.186
#Sta/Elev= 30
       0 1867.39    65.5 1853.46   111.3 1835.91   189.9 1817.09   252.1 1806.35
   337.2 1801.67  400.141786.921  488.841782.582  547.981780.421   576.2 1780.31
  607.111774.546   962.4 1769.19  1031.2 1769.31  1083.6 1772.93  1152.3 1769.86
  1266.9 1769.69  1335.6 1773.01  1345.4 1770.68  1358.5 1765.97  1384.6 1770.28
 1407.351768.805  1414.1 1769.62  1453.4 1795.03  1476.2 1792.37  1613.6  1798.5
  1675.8 1805.81  1698.7 1814.64  1770.7 1819.04  1783.8 1822.49  1826.3 1849.18
#Mann= 8 ,-1 , 0
       0     .12       0  400.14    .016       0  488.84     .12       0
  547.98    .016       0  607.11     .12       0  1345.4     .04       0
  1384.6    .016       0 1407.35     .12       0
#XS Ineff= 2 , 0
         1338.53 1799.68
Permanent Ineff=
       F       F
Bank Sta=1345.4,1384.6
XS Rating Curve= 0 ,0
Exp/Cntr=0.5,0.3