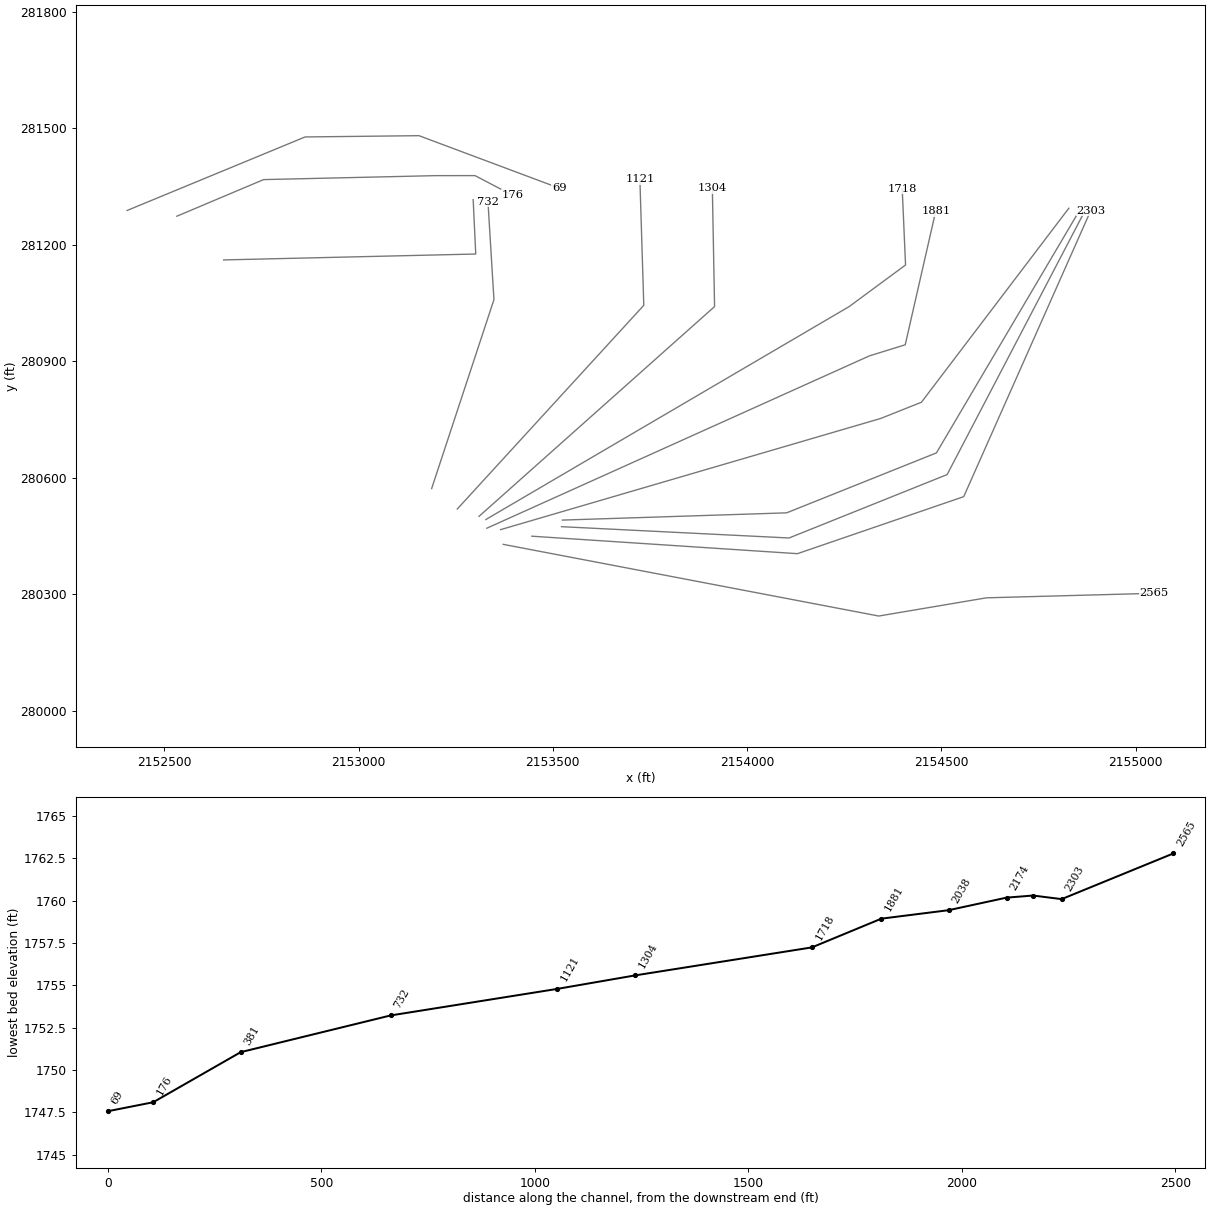
HEC-RAS study HARTSRN.prj: HARTSRN

--- HARTSRN.g01 (geometry) --- (continued)

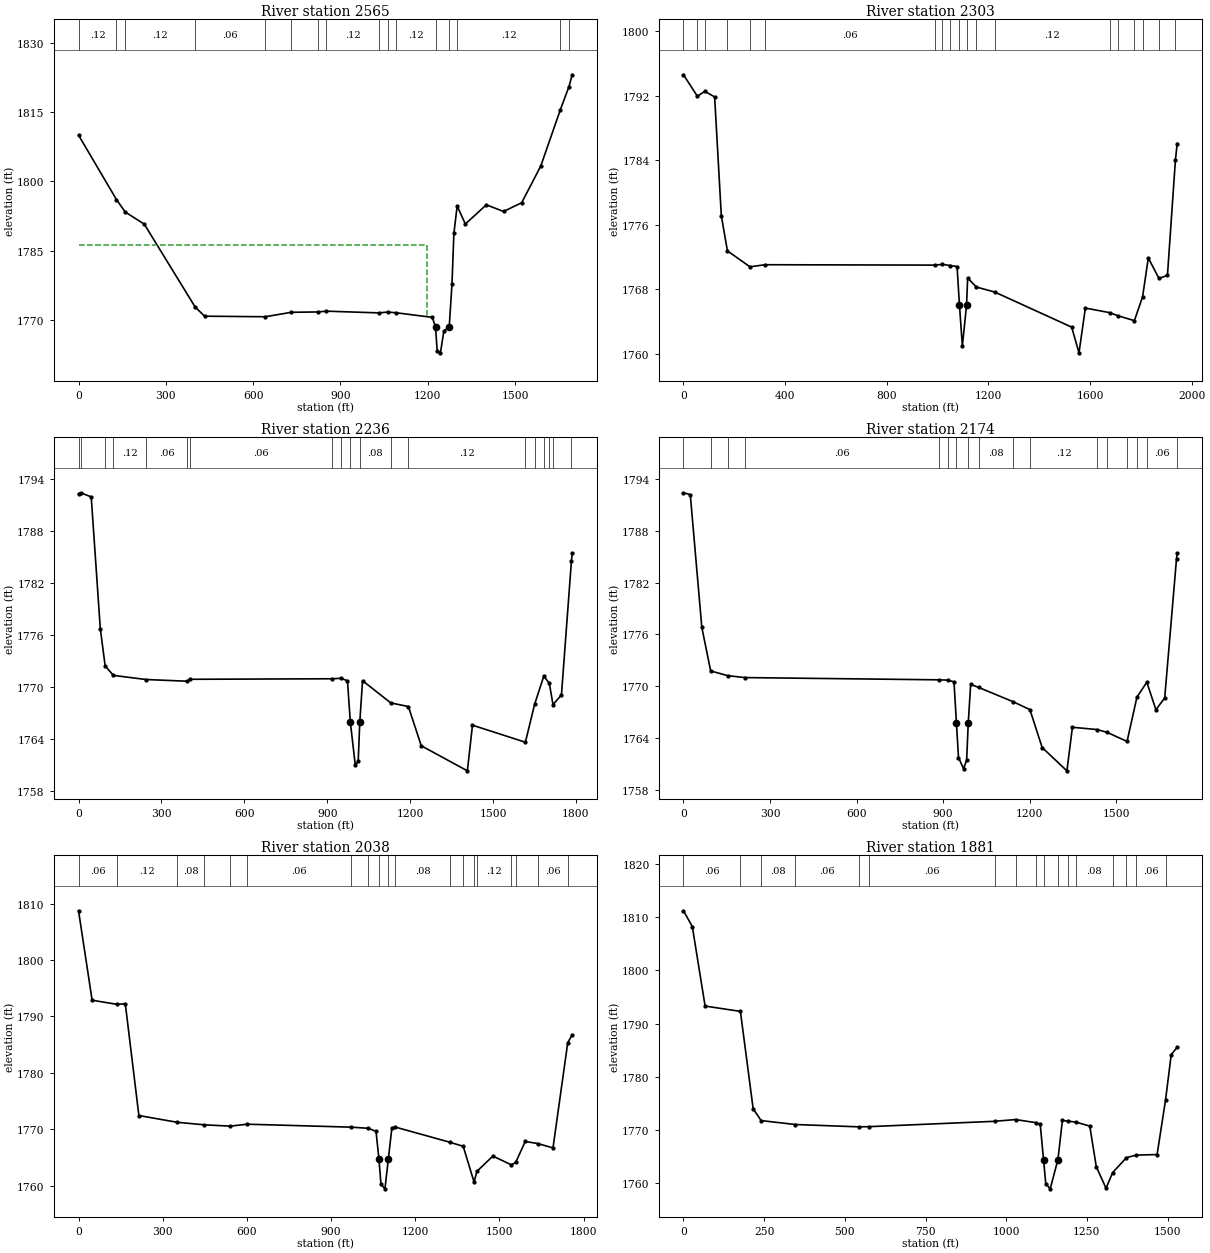
Type RM Length L Ch R = 1 ,2565    ,261.8,261.8,261.8
XS GIS Cut Line= 4
      2153372.32      280428.953     2154338.806      280244.467
      2154616.15      280291.3422155047.51997769280302.990160927
#Sta/Elev= 30
       01810.046  130.251796.073  160.321793.369 226.0611790.717  400.881772.727
 433.1461770.741  641.44 1770.62  731.66 1771.59  821.871771.661  851.941771.832
 1032.181771.459 1062.131771.632 1092.091771.4841215.6991770.486 1226.861768.437
1232.7771763.144 1243.791762.7851255.5471767.528 1274.041768.4361283.466 1777.69
 1290.031788.694 1301.281794.6691329.4151790.7511401.6191794.9251460.6961793.475
1523.0541795.3731588.6951803.348 1655.851815.553 1685.391820.5511696.7411823.152
#Mann= 16 ,-1 , 0
       0     .12       0  130.25     .06       0  160.32     .12       0
  400.88     .06       0  641.44     .08       0  731.66     .06       0
  821.87     .08       0  851.94     .12       0 1032.18     .06       0
 1062.13     .08       0 1092.09     .12       0 1226.86     .04       0
 1274.04    .016       0 1301.28     .12       0 1655.85     .08       0
 1685.39     .12       0
#XS Ineff= 2 , 0
         1198.66 1786.11
Permanent Ineff=
       F       F
Bank Sta=1226.86,1274.04
XS Rating Curve= 0 ,0
Exp/Cntr=0.5,0.3

Type RM Length L Ch R = 1 ,2303    ,66.8,66.8,66.8
XS GIS Cut Line= 4
     2153445.838      280449.958     2154129.518      280404.995
     2154557.556      280551.7592154884.33006322281287.744634687
#Sta/Elev= 30
       01794.576   54.531791.916   84.131792.524 122.5521791.824 148.8551777.094
  172.931772.726  261.741770.755  320.941771.016  987.891770.968 1019.121771.057
 1050.341770.9171076.6871770.791 1085.981766.0491097.4971760.957 1114.05    1766
1118.3071769.375 1152.471768.252 1225.251767.6221527.7371763.2761556.4541760.086
1581.5821765.643 1677.531765.069 1709.851764.687 1774.481764.078  1806.8 1767.04
 1829.271771.851 1871.441769.3081904.6531769.705 1936.071784.0321942.9251786.046
#Mann= 19 ,-1 , 0
       0     .12       0   54.53     .06       0   84.13     .12       0
  172.93     .06       0  261.74     .12       0  320.94     .06       0
  987.89     .08       0 1019.12     .06       0 1050.34     .12       0
 1085.98     .04       0 1114.05     .06       0 1152.47    .016       0
 1225.25     .12       0 1677.53     .06       0 1709.85     .12       0
 1774.48     .06       0  1806.8    .016       0 1871.44     .06       0
 1936.07    .016       0
Bank Sta=1085.98,1114.05
XS Rating Curve= 0 ,0
Exp/Cntr=0.3,0.1

Type RM Length L Ch R = 1 ,2236    ,62.2,62.2,62.2
XS GIS Cut Line= 4
2153522.25902228      280474.464     2154107.934      280445.377
2154514.81326946280608.5844232992154867.72862592281284.037109346
#Sta/Elev= 30
       01792.338    7.541792.433  45.923 1791.96  78.7721776.732   96.261772.443
  125.831771.331  244.121770.851  391.991770.659  404.571770.878   918.21770.939
  950.021770.993 973.3521770.708   983.81765.9111001.6311760.9661012.2361761.394
 1017.91  1765.91027.9691770.718 1130.05 1768.15 1193.831767.729 1240.511763.196
1407.3441760.2981425.8521765.573 1617.371763.604  1650.71767.988 1684.031771.247
 1704.021770.409 1717.351767.9491747.8971769.072    1784 1784.541786.882 1785.43
#Mann= 19 ,-1 , 0
       0     .06       0    7.54     .12       0   96.26     .06       0
  125.83     .12       0  244.12     .06       0  391.99     .08       0
  404.57     .06       0   918.2     .08       0  950.02     .12       0
   983.8     .04       0 1017.91     .08       0 1130.05    .016       0
 1193.83     .12       0 1617.37     .06       0  1650.7    .016       0
 1684.03     .06       0 1704.02    .016       0 1717.35     .06       0
    1784    .016       0
Bank Sta=983.8,1017.91
XS Rating Curve= 0 ,0
Exp/Cntr=0.3,0.1

Type RM Length L Ch R = 1 ,2174    ,135.6,135.6,135.6
XS GIS Cut Line= 4
2153524.35093347280491.434663004     2154101.661      280510.076
2154487.27176556280664.3690245232154852.61002704281283.478286261
#Sta/Elev= 30
       01792.414   23.521792.203  63.4921776.823   94.091771.759   153.21771.211
   212.31770.987  884.241770.727  916.051770.695 937.8921770.488   946.41765.736
 953.5211761.709  971.191760.419 981.7911761.433  987.33  1765.7 995.7891770.198
 1023.551769.844 1143.041768.186 1201.151767.2711243.7031762.8741329.4871760.174
1348.5341765.226 1435.121764.958 1469.411764.627 1538.011763.583 1572.311768.723
  1606.61770.4491638.0541767.261 1668.531768.625  1709.51784.7611711.8111785.411
#Mann= 17 ,-1 , 0
       0     .12       0   94.09     .06       0   153.2     .12       0
   212.3     .06       0  884.24     .08       0  916.05     .12       0
   946.4     .04       0  987.33     .12       0 1023.55     .08       0
 1143.04    .016       0 1201.15     .12       0 1435.12     .06       0
 1469.41     .12       0 1538.01     .06       0 1572.31    .016       0
  1606.6     .06       0  1709.5    .016       0
Bank Sta=946.4,987.33
XS Rating Curve= 0 ,0
Exp/Cntr=0.3,0.1

Type RM Length L Ch R = 1 ,2038    ,157.5,157.5,157.5
XS GIS Cut Line= 4
2153365.49463192280466.8734551112154344.06974561280753.103379857
2154448.69610283280794.7915032642154828.06359158281294.173280497
#Sta/Elev= 30
       01808.742  48.4051792.881 135.9181792.159 166.6831792.241 215.0221772.433
 351.2711771.236  448.141770.786  540.461770.552  602.011770.895  971.291770.371
 1033.281770.1681060.1621769.607 1070.511764.739 1077.821760.2411091.9471759.433
 1104.01 1764.721116.6681770.224 1128.661770.387 1322.061767.713 1370.881766.973
 1409.551760.635  1419.71762.541 1476.611765.2441542.5331763.689 1557.931764.125
1591.9751767.8341636.0611767.4691690.8591766.694  1743.41785.365 1759.341786.745
#Mann= 19 ,-1 , 0
       0     .06       0 135.918     .12       0 351.271     .08       0
  448.14     .06       0  540.46     .08       0  602.01     .06       0
  971.29     .08       0 1033.28     .12       0 1070.51     .04       0
 1104.01     .06       0 1128.66     .08       0 1322.06    .016       0
 1370.88     .12       0 1409.55     .08       0  1419.7     .12       0
1542.533     .06       0 1557.93    .016       01636.061     .06       0
  1743.4    .016       0
Bank Sta=1070.51,1104.01
XS Rating Curve= 0 ,0
Exp/Cntr=0.3,0.1

Type RM Length L Ch R = 1 ,1881    ,162.7,162.7,162.7
XS GIS Cut Line= 4
2153329.99382045280470.5365837812154314.78751112280914.155669578
2154406.98449784280942.6456171942154485.61624263281287.168084502
#Sta/Elev= 30
       0 1811.21   27.351808.236  66.9981793.294  176.381792.294 215.8471773.987
 240.6551771.764  346.871771.025  543.071770.589  575.461770.625  964.19 1771.63
 1028.981771.958 1093.151771.3651105.5691771.044 1115.781764.4481122.7391759.912
1136.4741758.9331160.439 1764.441174.247 1771.79 1190.861771.675 1216.47 1771.47
1259.1291770.733 1279.32 1763.081309.6071759.0351329.7981761.971 1372.641764.799
 1402.941765.2751467.7721765.379 1493.831775.6021511.5191784.156 1529.981785.558
#Mann= 17 ,-1 , 0
       0     .06       0  176.38     .12       0 240.655     .08       0
  346.87     .06       0  543.07     .08       0  575.46     .06       0
  964.19     .12       0 1028.98     .06       0 1093.15     .12       0
 1115.78     .04       01160.439     .12       0 1190.86     .06       0
 1216.47     .08       01329.798     .12       0 1372.64    .016       0
 1402.94     .06       0 1493.83     .08       0
Bank Sta=1115.78,1160.439
XS Rating Curve= 0 ,0
Exp/Cntr=0.3,0.1

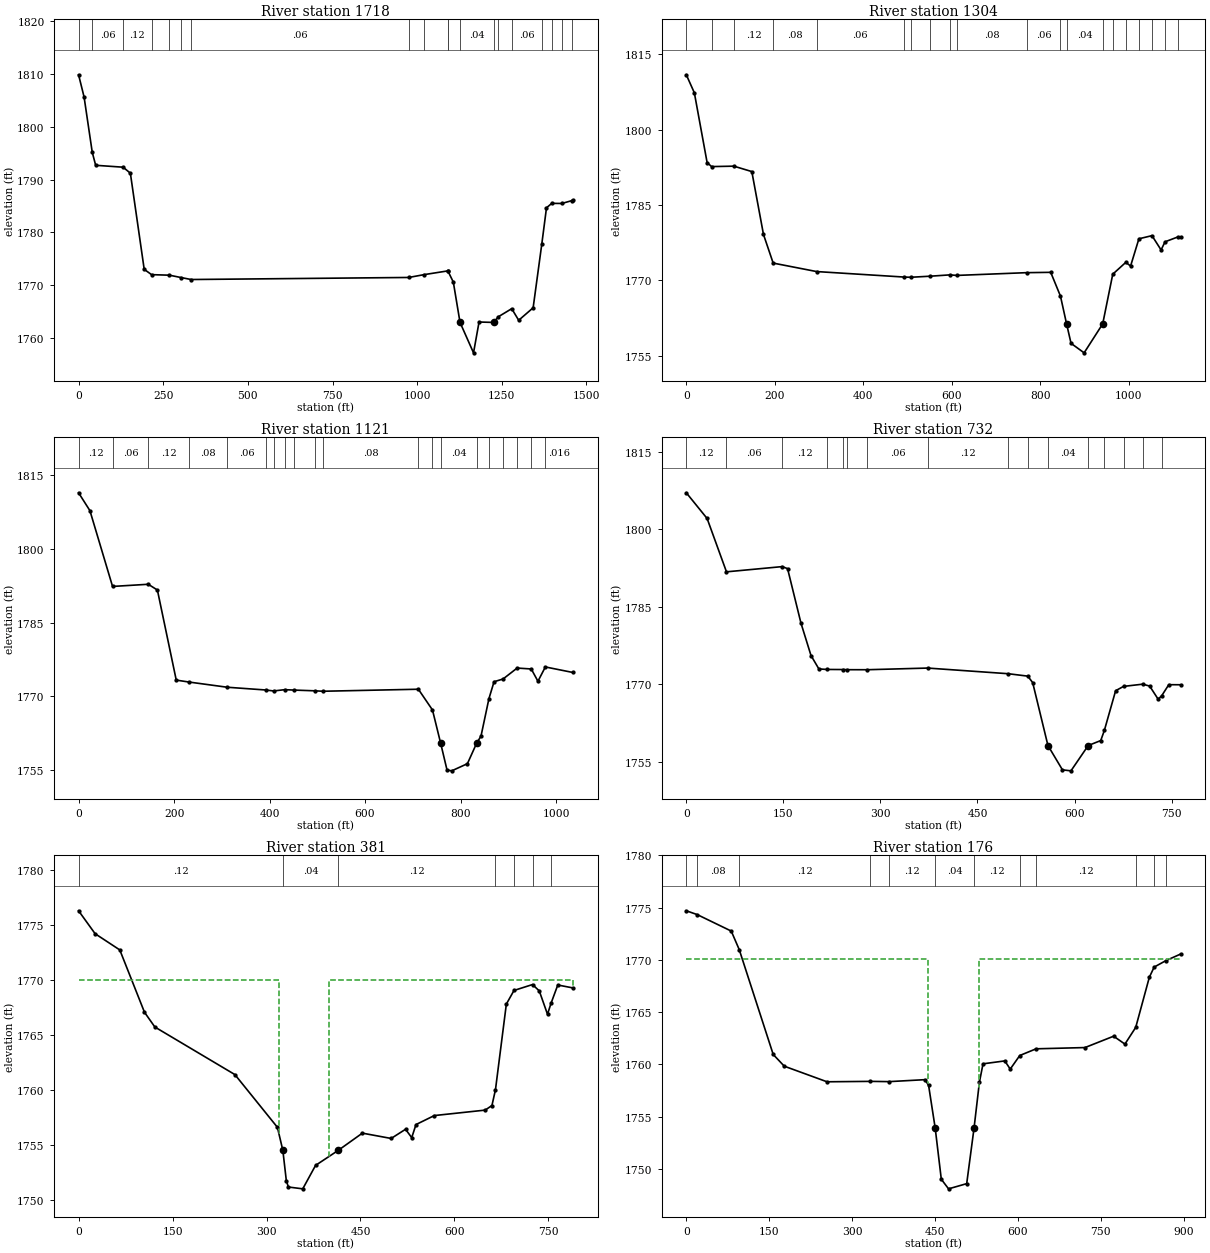
Type RM Length L Ch R = 1 ,1718    ,414.3,414.3,414.3
XS GIS Cut Line= 4
2153327.71077447280492.9925378072154262.73020535281041.045352388
     2154407.816      281148.1132154399.21236941 281344.01167585
#Sta/Elev= 30
       01809.824  16.2711805.625   40.421795.157  50.4971792.705  131.521792.346
 152.9821791.213 193.8621773.022  215.671772.023  268.461771.921  302.691771.476
  332.511771.103  975.091771.491 1021.631772.038 1090.561772.734 1090.721772.729
1106.8311770.622 1126.641762.9881166.5081757.2361182.8181763.066 1226.011762.988
 1239.961764.066 1279.321765.5881299.9041763.3941342.596 1765.76 1368.021777.752
1382.0041784.665 1397.581785.508 1427.151785.485 1456.721786.0191460.2031786.092
#Mann= 19 ,-1 , 0
       0     .12       0   40.42     .06       0  131.52     .12       0
  215.67     .08       0  268.46     .06       0  302.69     .08       0
  332.51     .06       0  975.09     .12       0 1021.63     .06       0
 1090.56     .12       0 1090.72     .06       0 1126.64     .04       0
 1226.01     .12       0 1239.96    .016       0 1279.32     .06       0
 1368.02     .08       0 1397.58    .016       0 1427.15     .08       0
 1456.72    .016       0
Bank Sta=1126.64,1226.01
XS Rating Curve= 0 ,0
Exp/Cntr=0.3,0.1

Type RM Length L Ch R = 1 ,1304    ,183.1,183.1,183.1
XS GIS Cut Line= 3
2153309.92244803280501.0277929752153916.22376383281041.045352388
2153910.48280704281346.309698798
#Sta/Elev= 30
       01810.891  18.1961807.302  47.0121793.437    57.11792.628  107.471792.714
 148.0631791.636 174.4241779.123   196.31773.433  294.411771.749  492.171770.656
  507.181770.613  551.591770.828  596.011771.091  610.831770.979  769.031771.528
 823.5151771.595  845.551766.864  859.361761.338 869.4551757.469 898.9881755.581
  940.99 1761.34  963.721771.227  993.261773.5841003.9931772.844  1022.81778.268
 1052.341778.8911072.902 1776.05 1081.891777.672 1111.431778.6531117.2421778.525
#Mann= 20 ,-1 , 0
       0     .12       0    57.1     .06       0  107.47     .12       0
   196.3     .08       0  294.41     .06       0  492.17     .08       0
  507.18     .06       0  551.59     .08       0  596.01     .06       0
  610.83     .08       0  769.03     .06       0  845.55     .12       0
  859.36     .04       0  940.99     .12       0  963.72    .016       0
  993.26     .08       0  1022.8    .016       0 1052.34     .06       0
 1081.89    .016       0 1111.43     .08       0
Bank Sta=859.36,940.99
XS Rating Curve= 0 ,0
Exp/Cntr=0.3,0.1

Type RM Length L Ch R = 1 ,1121    ,389,389,389
XS GIS Cut Line= 3
2153253.98075842280520.0089102232153734.02319364281044.298933998
2153723.97656988281368.744300799
#Sta/Elev= 30
       0 1811.43  23.7751807.786   71.171792.348  145.98 1792.79 165.0961791.615
 204.5721773.265  231.37 1772.87  311.471771.811  391.571771.255  408.391771.055
  431.621771.316  452.131771.231  495.861771.081  511.721770.995  711.681771.408
  741.231767.179   758.41760.388 771.7171754.938 781.5651754.781 814.3891756.239
   833.61760.388 842.8791761.868  859.441769.481  870.191772.939  888.991773.489
  918.54 1775.72  948.091775.534 962.0971773.031  977.641775.946 1035.461774.817
#Mann= 20 ,-1 , 0
       0     .12       0   71.17     .06       0  145.98     .12       0
  231.37     .08       0  311.47     .06       0  391.57     .12       0
  408.39     .06       0  431.62     .12       0  452.13     .08       0
  495.86     .06       0  511.72     .08       0  711.68     .06       0
  741.23     .12       0   758.4     .04       0   833.6     .12       0
  859.44    .016       0  888.99     .08       0  918.54    .016       0
  948.09     .06       0  977.64    .016       0
Bank Sta=758.4,833.6
XS Rating Curve= 0 ,0
Exp/Cntr=0.3,0.1

Type RM Length L Ch R = 1 ,732     ,351.1,351.1,351.1
XS GIS Cut Line= 3
2153187.96236958280572.6160454542153348.31109372281058.940051245
2153332.91522028281310.499916461
#Sta/Elev= 30
       01807.075  32.1621802.095   62.081791.763  148.321792.776 156.526 1792.38
 177.2541781.811 192.7281775.553  204.891772.956  217.581772.856  242.621772.837
  248.691772.809  279.791772.803  373.091773.125   497.51772.031   527.81771.561
 535.3421770.308  558.931758.123  581.361753.407 594.5081753.219  621.171758.122
 640.5261759.082  646.161761.063 663.5341768.736  675.761769.574  705.351770.004
 716.1261769.638 729.2741767.091  734.941767.803 745.7091769.905 764.1071769.892
#Mann= 16 ,-1 , 0
       0     .12       0   62.08     .06       0  148.32     .12       0
  217.58     .08       0  242.62     .06       0  248.69     .08       0
  279.79     .06       0  373.09     .12       0   497.5     .06       0
   527.8     .12       0  558.93     .04       0  621.17     .12       0
  646.16     .08       0  675.76    .016       0  705.35     .06       0
  734.94    .016       0
Bank Sta=558.93,621.17
XS Rating Curve= 0 ,0
Exp/Cntr=0.5,0.3

Type RM Length L Ch R = 1 ,381     ,204.9,204.9,204.9
XS GIS Cut Line= 3
     2152652.608      281161.134      2153301.48      281176.324
2153294.81267536281316.337817527
#Sta/Elev= 30
       01776.263  26.4191774.183    65.81772.713  105.181767.066 121.7881765.724
 249.5771761.409 317.3941756.631  326.09 1754.54  331.621751.803 334.9021751.216
 357.8741751.051 378.3211753.177  414.591754.542 453.0441756.101 498.9881755.619
  521.961756.452 531.8061755.693 538.654 1756.88 567.9051757.695  649.051758.189
 659.8871758.607  665.521760.043 682.8791767.803  695.091769.039  724.661769.574
 735.4321768.998  748.57 1766.88  754.231767.877 764.9921769.533 789.2221769.268
#Mann= 7 ,-1 , 0
       0     .12       0  326.09     .04       0  414.59     .12       0
  665.52     .08       0  695.09    .016       0  724.66     .06       0
  754.23    .016       0
#XS Ineff= 2 , 0
          320.71    1770  399.11            1770
Permanent Ineff=
       F       F
Bank Sta=326.09,414.59
XS Rating Curve= 0 ,0
Exp/Cntr=0.5,0.3

Type RM Length L Ch R = 1 ,176     ,106.4,106.4,106.4
XS GIS Cut Line= 5
2152532.10562617281273.645184792 2152755.3458452281367.867625163
2153197.60379927281378.0807578562153299.65123584      281378.147
2153395.01626997281328.144591797
#Sta/Elev= 30
       01774.689   19.781774.323    81.31772.748   95.751770.975 157.2351760.945
 177.2691759.824 254.5691758.333  333.221758.373  366.921758.348 431.7821758.536
 438.3451757.988  450.311753.892 461.3171749.012 474.4441748.094 507.261 1748.59
  520.531753.892 530.2331758.284 536.7961760.051 576.177 1760.33 586.0221759.547
  603.281760.846  632.821761.487  721.231761.606 773.0561762.692 793.5161761.937
  813.071763.539 837.7181768.337  846.421769.304  867.891769.928 894.4121770.554
#Mann= 12 ,-1 , 0
       0    .016       0   19.78     .08       0   95.75     .12       0
  333.22     .06       0  366.92     .12       0  450.31     .04       0
  520.53     .12       0  603.28     .06       0  632.82     .12       0
  813.07     .08       0  846.42     .12       0  867.89    .016       0
#XS Ineff= 2 , 0
          436.53 1770.06  528.95         1770.06
Permanent Ineff=
       F       F
Bank Sta=450.31,520.53
XS Rating Curve= 0 ,0
Exp/Cntr=0.5,0.3

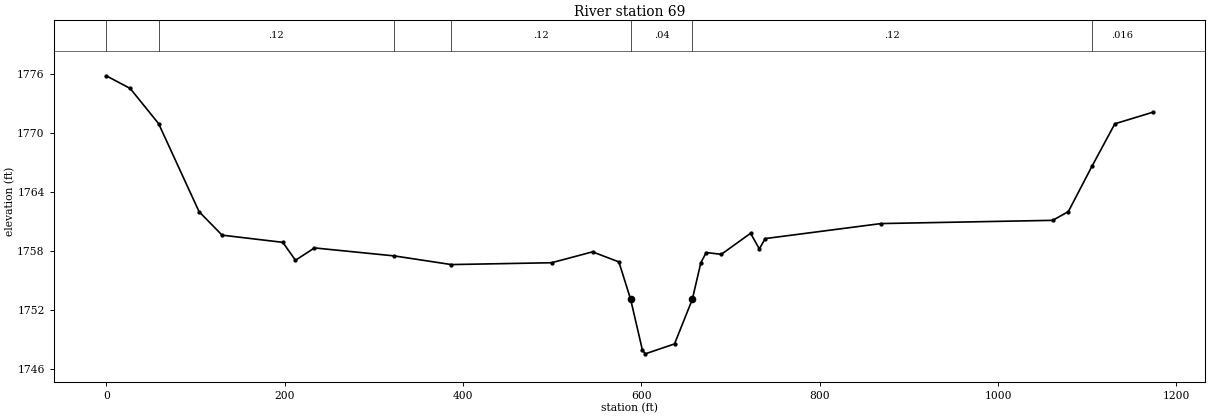
Type RM Length L Ch R = 1 ,69      ,73.6,80.8,87.9
XS GIS Cut Line= 4
2152404.12568819281288.449034409 2152862.2260011281477.676004518
 2153155.3542639281480.9491917922153516.02571476281346.014719915
#Sta/Elev= 30
       01775.847  26.8431774.563   58.721770.987 104.1851762.018 129.9651759.636
 198.0311758.904  212.23 1757.08 233.5281758.337  323.041757.524  386.961756.643
 499.445 1756.83  545.381757.938 574.9091756.912  588.071753.101 601.1571747.983
 604.4381747.563 637.249 1748.57  657.221753.104 666.778 1756.83 672.8291757.868
 689.7451757.686 722.5561759.825 732.3991758.239 738.9611759.287  868.851760.814
1061.3621761.1431078.8771762.034 1105.41 1766.651131.0161770.9621173.8761772.147
#Mann= 7 ,-1 , 0
       0     .06       0   58.72     .12       0  323.04     .06       0
  386.96     .12       0  588.07     .04       0  657.22     .12       0
 1105.41    .016       0
Bank Sta=588.07,657.22
XS Rating Curve= 0 ,0
Exp/Cntr=0.3,0.1
LCMann Table=0

Chan Stop Cuts=-1
Use User Specified Reach Order=0
Composite Channel Slope=5